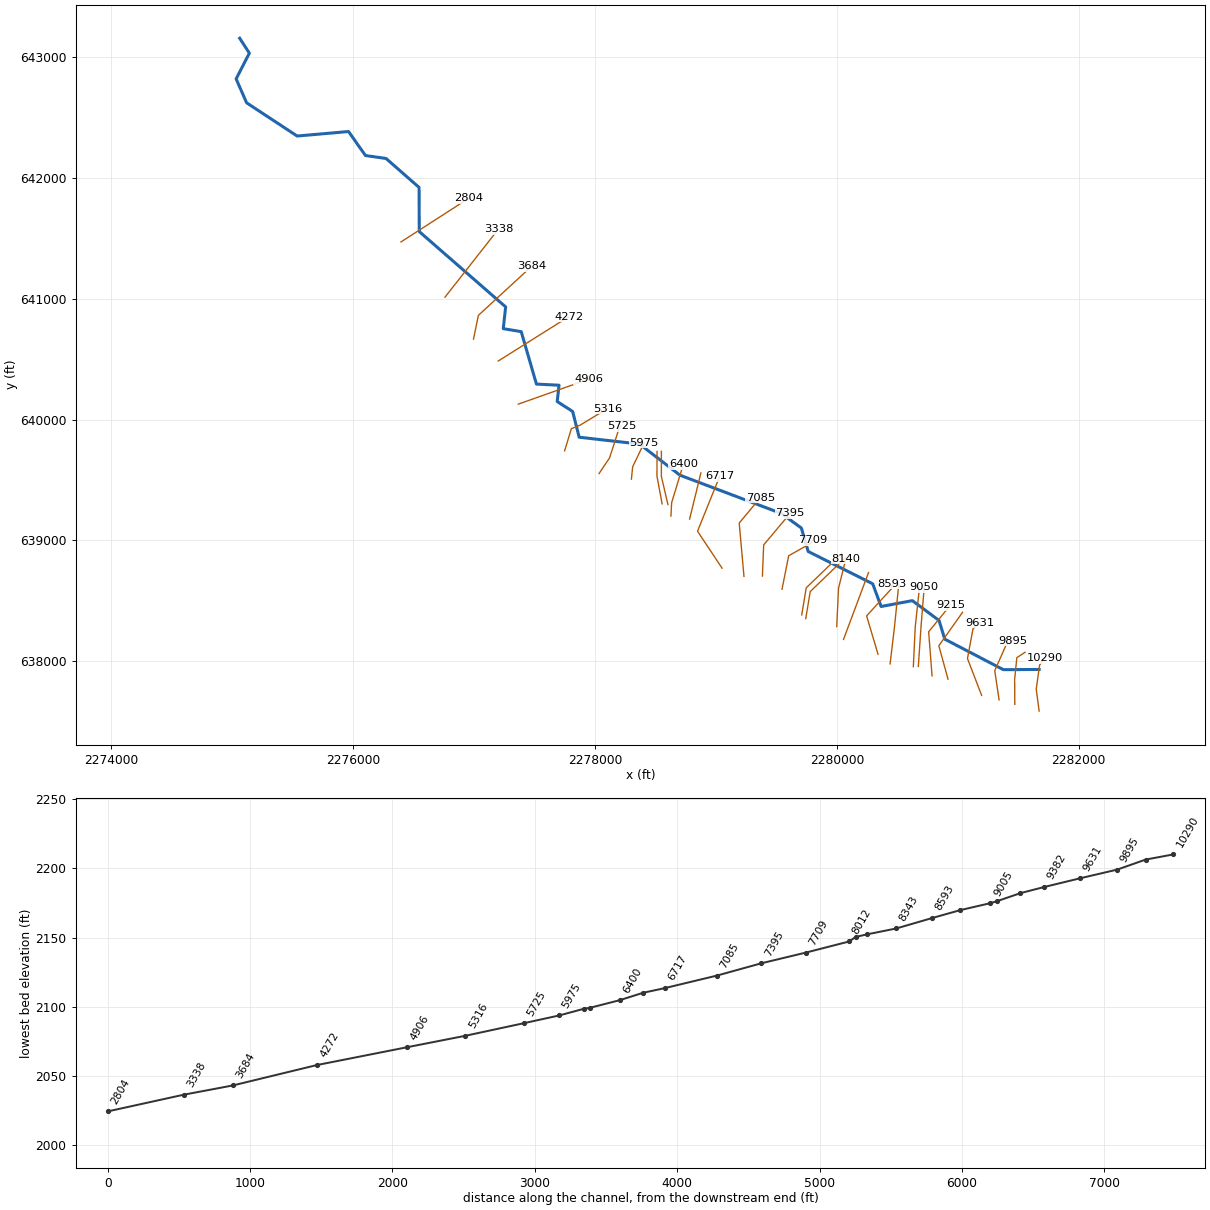
--- CRWFRDRN.prj (project) ---

Proj Title=CRWFRDRN
Current Plan=p01
Default Exp/Contr=0,0
English Units
Geom File=g01
Flow File=f01
Plan File=p01
BEGIN DESCRIPTION:
----------MODEL BY WOOD PLC 2022----------
AFH study
Randolph County, WV
HEC-RAS Version: RAS 6.2
Vertical Datum: NAVD88
Projection: NAD 1983 StatePlane West Virginia S FIPS 4702 (US Feet)
Terrain: 1-meter LIDAR (FEMA Region III 3DEP collected 2016-2018)
Land Use: 2019 NLCD
Hydrologic Method:
WV SIR2010-5033 regression equations
Additional Model Notes:
None
END DESCRIPTION:
DSS Export Rating Curves= 0
DSS Export Rating Curve Sorted= 0
DSS Export Volume Flow Curves= 0
DXF OffsetX= 0
DXF OffsetY= 0
DXF ScaleX= 0
DXF ScaleY= 0

--- CRWFRDRN.p01 (plan) ---

Plan Title=Floodplain
Program Version=6.20
Short Identifier=Floodplain
Geom File=g01
Flow File=f01
Subcritical Flow
K Sum by GR= 0
Std Step Tol= 0.01
Critical Tol= 0.01
Num of Std Step Trials= 20
Max Error Tol= 0.3
Flow Tol Ratio= 0.001
Split Flow NTrial= 30
Split Flow Tol= 0.02
Split Flow Ratio= 0.02
Log Output Level= 0
Friction Slope Method= 1
Unsteady Friction Slope Method= 2
Unsteady Bridges Friction Slope Method= 1
Parabolic Critical Depth
Global Vel Dist= 0 , 0 , 0
Global Log Level= 0
CheckData=True
Encroach Param=-1 ,0,0, 0
Mapping Interval=1HOUR
Computation Time Step Use Courant=        0
Computation Time Step Use Time Series=    0
Computation Time Step Count To Double=0
Computation Time Step Max Doubling=0
Computation Time Step Max Halving=0
Computation Time Step Residence Courant=0
Run HTab= 0
Run UNet= 0
Run Sediment= 0
Run PostProcess= 0
Run WQNet= 0
Run RASMapper=-1
UNET Theta= 0
UNET Theta Warmup= 0
UNET ZTol= 0
UNET ZSATol= 0
UNET MxIter= 0
UNET Max Iter WO Improvement= 0
UNET MaxInSteps= 0
UNET DtIC= 0
UNET DtMin= 0
UNET MaxCRTS= 0
UNET WFStab= 0
UNET SFStab= 0
UNET WFX= 1
UNET SFX= 1
UNET Gravity=32.174
UNET 1D Methodology=Finite Difference
UNET DSS MLevel= 1
UNET Pardiso=0
UNET DZMax Abort= 0
UNET Use Existing IB Tables= 0
UNET Froude Reduction=False
UNET Froude Limit= 0
UNET Froude Power= 0
UNET D1 Cores= 0
UNET WindReference=Eulerian
UNET WindDragFormulation=Hsu (1988)
UNET D2 Coriolis=0
UNET D2 Cores= 0
UNET D2 Theta= 1
UNET D2 Theta Warmup= 1
UNET D2 Z Tol= 0.01
UNET D2 Volume Tol= 0.01
UNET D2 Max Iterations= 20
UNET D2 Equation= 0
UNET D2 RampUpFraction=0.1
UNET D2 TimeSlices= 1
UNET D2 Turbulence Formulation=Non-Conservative (original)
UNET D2 Eddy Viscosity=0.3
UNET D2 Transverse Eddy Viscosity=0.1
UNET D2 Smagorinsky Mixing=0
UNET D2 BCVolumeCheck=0
UNET D2 Cores=0
UNET D2 SolverType=PARDISO (Direct)
UNET D2 Minimum Iterations= 2147483647
UNET D2 Maximum Iterations= 2147483647
UNET D2 Restart Number= 10
UNET D2 Relaxation Coeff=1.3
UNET D2 SOR Precondition Iterations= 10
UNET D2 ILUT Maximum Fill= 8
UNET D2 ILUT Tolerance=1E-08
UNET D1D2 MaxIter= 0
UNET D1D2 ZTol=0.01
UNET D1D2 QTol=0.1
UNET D1D2 MinQTol=1
Write IC File= 0
Write IC File at Fixed DateTime=0
Write IC File at Sim End=0
Echo Input=False
Echo Parameters=False
Echo Output=False
Write Detailed= 0
HDF Write Warmup=0
HDF Write Time Slices=0
HDF Flush=0
HDF Compression= 1
HDF Chunk Size= 1
HDF Spatial Parts= 1
HDF Use Max Rows=0
HDF Fixed Rows= 1
Calibration Method= 0
Calibration Iterations= 20
Calibration Max Change=0.05
Calibration Tolerance=0.2
Calibration Maximum=1.5
Calibration Minimum=0.5
Calibration Optimization Method= 1
WQ AD Non Conservative
WQ ULTIMATE=-1
WQ Max Comp Step=1HOUR
WQ Output Interval=15MIN
WQ Output Selected Increments= 0
WQ Output face flow=0
WQ Output face velocity=0
WQ Output face area=0
WQ Output face dispersion=0
WQ Output cell volume=0
WQ Output cell surface area=0
WQ Output cell continuity=0
WQ Output cumulative cell continuity=0
WQ Output face conc=0
WQ Output face dconc_dx=0
WQ Output face courant=0
WQ Output face peclet=0
WQ Output face adv mass=0
WQ Output face disp mass=0
WQ Output cell mass=0
WQ Output cell source sink temp=0
WQ Output nsm pathways=0
WQ Output nsm derived pathways=0
WQ Create Restart=0
WQ Fixed Restart=0
WQ System Summary=0
WQ Write To DSS=0
Sorting and Armoring Iterations= 10
XS Update Threshold= 0.02
Bed Roughness Predictor= 0
Hydraulics Update Threshold= 0.02
Energy Slope Method= 1
Volume Change Method= 1
Sediment Retention Method= 0
Sediment TS Multiplier= 1
Warm Up Method= 0
XS Weighting Method= 0
Number of US Weighted Cross Sections= 1
Number of DS Weighted Cross Sections= 1
Upstream XS Weight=0
Main XS Weight=1
Downstream XS Weight=0
Number of DS XS's Weighted with US Boundary= 1
Upstream Boundary Weight= 1
Weight of XSs Associated with US Boundary= 0
Number of US XS's Weighted with DS Boundary= 1
Downstream Boundary Weight= 0.5
Weight of XSs Associated with DS Boundary= 0.5
Percentile Method= 0
Sediment Output Level= 3
Mass or Volume Output= 0
Output Increment Type= 1
Profile and TS Output Increment= 1
Transport Output Increment 1
XS Output Flag= 0
XS Output Increment= 10
Read HDF5 Sediment Hotstart= 0
Sediment Hotstart Type= 0
Write Gradation File= 0
Read Gradation Hotstart= 0
Write HDF5 File= 1
Write Binary Output= 1
Write DSS Sediment File= 0
DSS Sediment Output Type= 1
SV Curve= 0
Specific Gage Flag= 0
Subcell Erosion Methods= 0
Subcell Deposition Methods= 0
Advection Scheme= 1
Matrix Solver= 0
Implicit Weighting Factor= 1
Maximum Outer Loop Convergence Iterations= 5
Convergence Maximum Absolute= 0.001
Convergence RMSE= 0.0001
Grain Fractions Max Abs Error= 0.001
Max Subgrid Regions= 1
Max Subgrid Length Scale= 3.402823E+38
Initial Layer Thickness= 3.402823E+38
Min Layer Thickness= 3.402823E+38
Max Layer Thickness= 3.402823E+38
Number of Layers= 5

--- CRWFRDRN.f01 (steady flow) ---

Flow Title=Flow
Program Version=6.20
Number of Profiles= 1
Profile Names=P100yr
River Rch & RM=CRWFRDRN,Main            ,10290
     338
River Rch & RM=CRWFRDRN,Main            ,5725
     377
River Rch & RM=CRWFRDRN,Main            ,1269
     529
Boundary for River Rch & Prof#=CRWFRDRN,Main            , 1
Up Type= 0
Dn Type= 3
Dn Slope=0.0156
DSS Import GetInterval= 0
DSS Import GetPeak= 0
DSS Import FillOption= 0

--- CRWFRDRN.g01 (geometry) ---

Geom Title=Geometry
Program Version=6.20

River Reach=CRWFRDRN        ,Main
Reach XY= 30
     2281672.816      637932.127      2281376.81      637930.391
     2280891.567      638182.995     2280844.692      638337.509
     2280623.743      638501.523     2280365.525      638452.961
      2280296.08      638640.461     2279762.468      638908.293
     2279705.905      639102.0442279540.96524404639222.433629453
     2278701.627      639539.347     2278368.129      639796.711
 2277868.3741522639853.487703361      2277814.31      640066.676
     2277686.769      640148.486     2277701.614      640283.667
     2277515.108      640292.869     2277389.145      640726.866
     2277240.571      640751.433      2277260.49       640931.26
     2276546.081      641554.523     2276544.344      641919.975
     2276270.907      642159.558     2276100.768      642183.864
     2275961.185      642382.301     2275536.026      642345.062
     2275118.169      642619.854     2275031.453      642817.551
     2275140.849      643030.885     2275060.677      643154.164

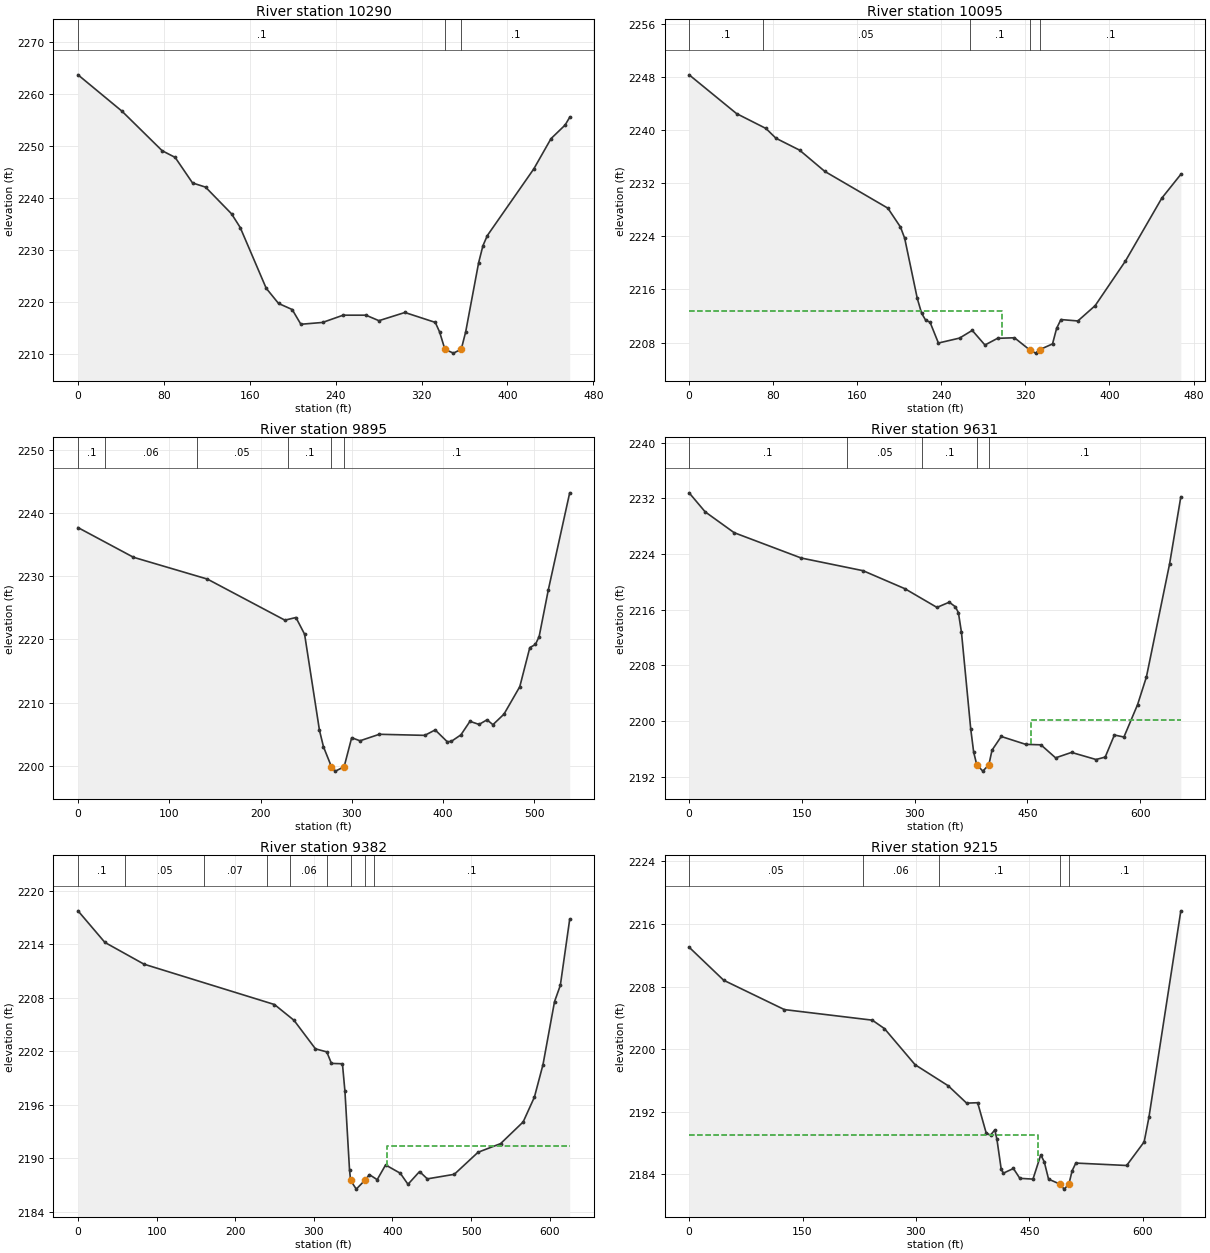
Type RM Length L Ch R = 1 ,10290   ,194.7,194.8,194.7
XS GIS Cut Line= 4
2281672.52233329637587.4238403522281648.32187049637769.099148893
2281676.38362057637969.2520775362281720.41187444638027.016421828
#Sta/Elev= 30
       0 2263.76      41 2256.75    78.4 2249.14    90.5 2247.85   106.7 2242.93
   118.8 2242.13     143 2236.99   151.1 2234.35   175.3 2222.65   186.8 2219.72
   199.5 2218.55   207.6 2215.71   227.8 2216.06     247 2217.46   268.2 2217.46
   280.3  2216.4   304.5 2217.98   332.8 2216.07   336.8 2214.24  341.782210.874
   349.7 2210.15     357  2210.9   361.1 2214.23   373.2 2227.59   377.2 2230.85
   381.3  2232.8   424.6 2245.65   440.6 2251.47   453.7 2254.08     458 2255.58
#Mann= 3 ,-1,0
       0      .1       0  341.78    .045       0     357      .1       0
Bank Sta=341.78,357
XS Rating Curve= 0 ,0
Exp/Cntr(USF)=0,0
Exp/Cntr=0.3,0.1

Type RM Length L Ch R = 1 ,10095   ,200.1,199.4,193.6
XS GIS Cut Line= 4
2281471.05764629637644.0865757762281469.97702553637851.138042312
2281487.90638462638029.5425376572281556.01437861638074.394583272
#Sta/Elev= 30
       0 2248.29    45.1 2242.46    73.1 2240.22    82.6 2238.75   105.1 2236.96
   129.1 2233.76   189.1 2228.23   201.1 2225.39   205.1 2223.71   217.1 2214.65
   221.2 2212.43   225.2 2211.34   229.2 2211.09   237.2 2207.94   257.3 2208.68
   269.4 2209.84   281.5 2207.64   293.5 2208.65   309.6 2208.73   323.9 2206.93
   329.7 2206.42   333.7 2206.95   345.8 2207.81   349.7 2210.15   353.8 2211.47
   369.9 2211.26   386.4 2213.57   415.2 2220.28   449.8 2229.74   467.9 2233.32
#Mann= 5 ,-1,0
       0      .1       0      70     .05       0  267.05      .1       0
   323.9    .045       0   333.7      .1       0
#XS Ineff= 2 , 0
          297.63 2212.81
Permanent Ineff=
       F       F
Bank Sta=323.9,333.7
XS Rating Curve= 0 ,0
Exp/Cntr(USF)=0,0
Exp/Cntr=0.3,0.1

Type RM Length L Ch R = 1 ,9895    ,263.4,264.8,267.3
XS GIS Cut Line= 4
2281341.25176444637680.9685575832281305.29474546637922.228555876
2281396.49148878638129.0903299612281450.52340525638171.707052813
#Sta/Elev= 30
       0 2237.71    60.8 2233.01   141.8 2229.56   226.7 2223.06   238.8 2223.48
   248.3 2220.84   264.6 2205.63     269 2203.02   277.7 2199.87   282.1 2199.17
  291.63 2199.86   299.9 2204.46     309 2203.97   330.2    2205     380 2204.83
   391.4 2205.69   404.5 2203.84   408.9 2203.86   419.6 2204.91   429.5 2207.05
   439.5 2206.56   448.2 2207.29   454.7 2206.52   466.8 2208.19   484.1 2212.53
   495.1 2218.72   501.2 2219.21   505.3 2220.45   515.4 2227.87   538.8 2243.21
#Mann= 6 ,-1,0
       0      .1       0      30     .06       0     130     .05       0
     230      .1       0   277.7    .045       0  291.63      .1       0
Bank Sta=277.7,291.63
XS Rating Curve= 0 ,0
Exp/Cntr(USF)=0,0
Exp/Cntr=0.3,0.1

Type RM Length L Ch R = 1 ,9631    ,250.9,248.9,244
XS GIS Cut Line= 4
2281196.91233174637717.256585781 2281079.6331659638022.697929774
2281125.38183532638268.1607751852281182.88058838638319.740538955
#Sta/Elev= 30
       0 2232.78    21.3 2230.05    59.9 2227.05   149.1 2223.41   231.3 2221.59
     287    2219   329.7 2216.31     346 2217.06   354.1 2216.41   358.2 2215.56
   362.3 2212.71   374.6 2198.84   378.5 2195.52   382.6 2193.71   390.7 2192.78
  398.76  2193.7   402.9 2195.79   415.2 2197.76   447.7 2196.63     468 2196.56
   487.5 2194.69   508.7 2195.47   541.3 2194.45   553.5  2194.8   565.7 2197.97
   578.4 2197.68   596.6 2202.35   608.3 2206.31   639.1 2222.54   654.1 2232.21
#Mann= 5 ,-1,0
       0      .1       0     210     .05       0     310      .1       0
   382.6    .045       0  398.76      .1       0
#XS Ineff= 2 , 0
                          454.26         2200.11
Permanent Ineff=
       F       F
Bank Sta=382.6,398.76
XS Rating Curve= 0 ,0
Exp/Cntr(USF)=0,0
Exp/Cntr=0.3,0.1

Type RM Length L Ch R = 1 ,9382    ,174.4,166.5,168.8
XS GIS Cut Line= 3
2280918.78136753637852.1730202612280842.88642504638128.545169303
2281039.06769146638404.917318345
#Sta/Elev= 30
       0 2217.74    34.2  2214.2      84 2211.76   249.9 2207.24   274.8 2205.47
   302.1 2202.27   316.5 2201.93   322.4 2200.64   336.4  2200.6   339.6  2197.5
   345.4 2188.72   346.82187.521     354 2186.55   364.8 2187.53   370.8 2188.17
   380.6 2187.61   391.3 2189.26     410 2188.33   419.8 2187.09   434.5 2188.52
   444.4  2187.7   478.7 2188.21   508.9 2190.68   537.6 2191.65   566.3 2194.08
   580.6 2196.86   591.5 2200.49   606.2 2207.56   613.6 2209.39   625.5 2216.79
#Mann= 9 ,-1,0
       0      .1       0      60     .05       0     160     .07       0
     240     .05       0     270     .06       0   316.6     .05       0
   346.8    .045       0   364.8     .05       0   376.6      .1       0
#XS Ineff= 2 , 0
                          393.02         2191.42
Permanent Ineff=
       F       F
Bank Sta=346.8,364.8
XS Rating Curve= 0 ,0
Exp/Cntr(USF)=0,0
Exp/Cntr=0.3,0.1

Type RM Length L Ch R = 1 ,9215    ,163.9,165.5,170.3
XS GIS Cut Line= 3
 2280786.8288259637879.5910184672280758.54280028638243.773598283
2280938.86621359638464.758173414
#Sta/Elev= 30
       0 2213.04    45.7 2208.82     126 2205.07   242.3 2203.72   258.4 2202.64
     299 2198.02   342.7 2195.34   367.1 2193.12   381.7 2193.17     393  2189.3
   398.7 2189.03   404.4 2189.69   407.2 2188.49   412.9 2184.65   415.8 2184.17
     429 2184.77   437.5 2183.51   454.9 2183.41   465.2 2186.51   469.8 2185.63
   475.5 2183.41   490.42182.775   496.2 2182.13   502.42182.774   506.7 2184.48
   511.6 2185.46   578.8 2185.15     602 2188.17   608.3 2191.31   650.5 2217.69
#Mann= 5 ,-1,0
       0     .05       0     230     .06       0     330      .1       0
   490.4    .045       0   502.4      .1       0
#XS Ineff= 2 , 0
          462.02 2188.99
Permanent Ineff=
       F       F
Bank Sta=490.4,502.4
XS Rating Curve= 0 ,0
Exp/Cntr(USF)=0,0
Exp/Cntr=0.3,0.1

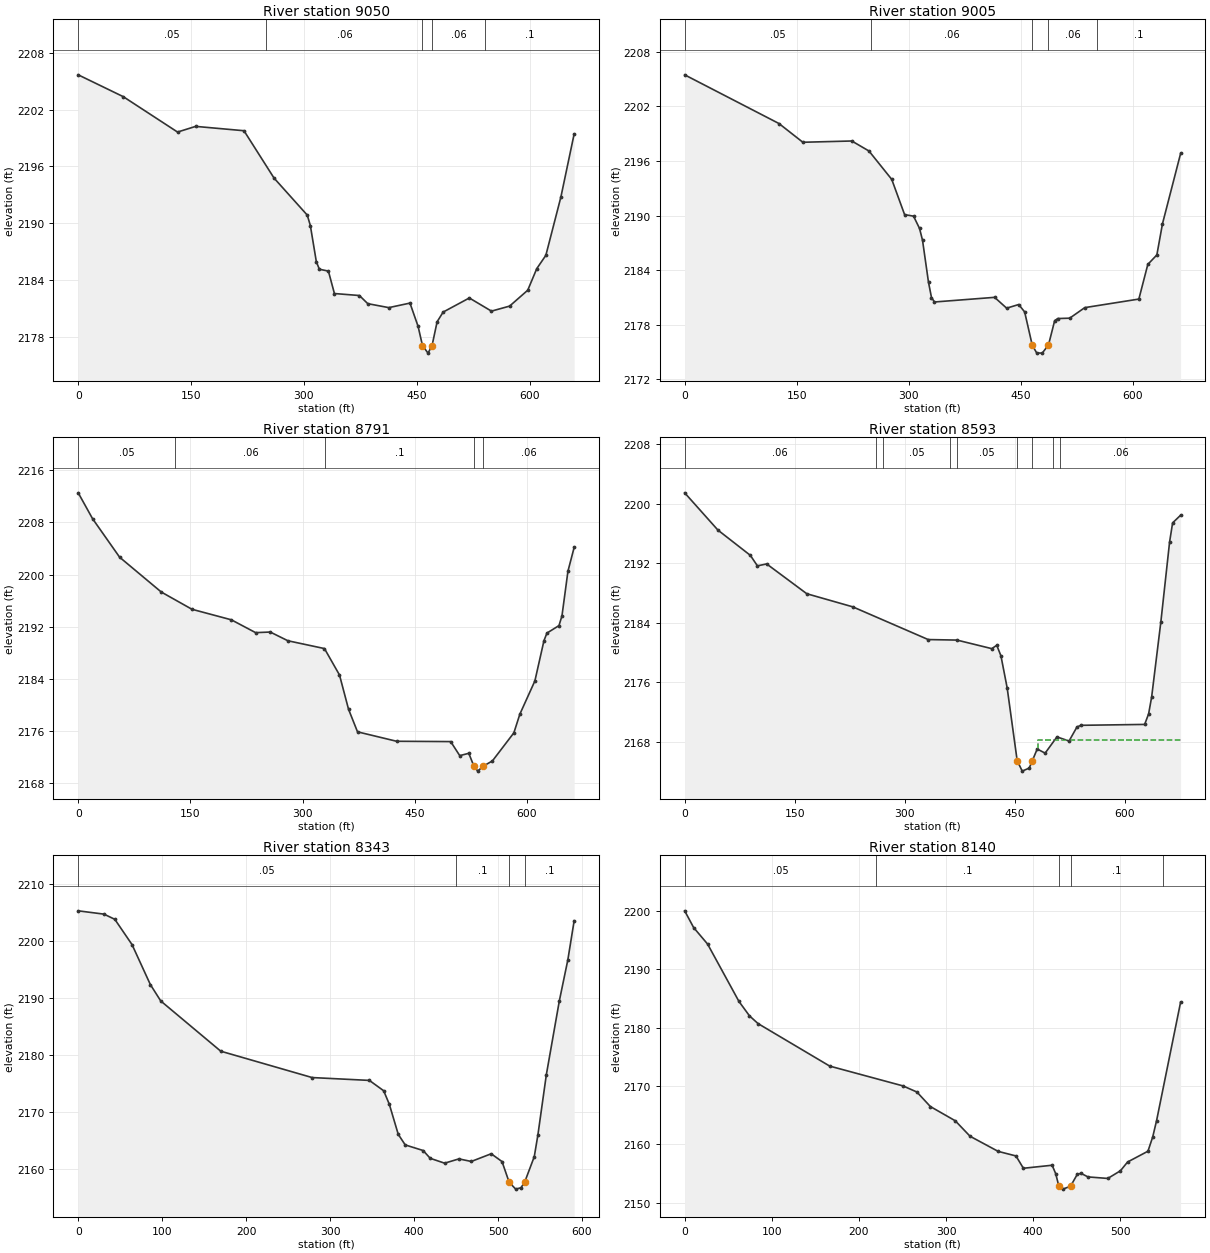
Type RM Length L Ch R = 1 ,9050    ,44.2,45.2,44.9
XS GIS Cut Line= 3
2280673.21271232637957.434160964 2280695.7152781638287.950307299
 2280722.1162209638614.727589076
#Sta/Elev= 30
       0 2205.69    59.9 2203.38     132 2199.64   156.1 2200.24   220.3 2199.78
   260.3 2194.77   304.4 2190.86   308.5 2189.76   316.5 2185.92   320.5 2185.14
   332.5 2184.94   340.5 2182.57   373.7 2182.36   384.8  2181.5   412.8 2181.08
   440.9 2181.56   451.7  2179.1  457.55 2177.06   464.9 2176.27   470.2 2177.05
     477 2179.59     485 2180.61   519.8  2182.1   549.2 2180.71   573.3 2181.24
   597.4 2182.92   609.4  2185.2   621.5 2186.61   641.5 2192.78   659.1 2199.44
#Mann= 5 ,-1,0
       0     .05       0     250     .06       0  457.55    .045       0
   470.2     .06       0  541.28      .1       0
Bank Sta=457.55,470.2
XS Rating Curve= 0 ,0
Exp/Cntr(USF)=0,0
Exp/Cntr=0.3,0.1

Type RM Length L Ch R = 1 ,9005    ,213.6,213.9,210.9
XS GIS Cut Line= 3
2280631.89257485637955.1667667322280647.90423322638286.182213637
2280683.26176524638616.775138033
#Sta/Elev= 30
       0 2205.46   126.2 2200.11   158.2 2198.05   223.7 2198.19   246.7 2197.09
   277.2 2193.97   294.4  2190.1   306.4 2189.93   314.4 2188.58   318.4 2187.28
   326.4 2182.66   330.4 2180.99   334.4  2180.5   414.9 2181.01     431 2179.82
   447.1 2180.22   455.1 2179.41   465.2 2175.78   471.2  2174.9   478.6 2174.88
     487 2175.77   495.3 2178.45   499.4 2178.68   515.4 2178.72   535.6 2179.88
     608 2180.82     620 2184.63   632.1 2185.67   639.6 2189.09   663.9 2196.82
#Mann= 5 ,-1,0
       0     .05       0     250     .06       0   465.2    .045       0
     487     .06       0   551.4      .1       0
Bank Sta=465.2,487
XS Rating Curve= 0 ,0
Exp/Cntr(USF)=0,0
Exp/Cntr=0.3,0.1

Type RM Length L Ch R = 1 ,8791    ,208.1,198,191.8
XS GIS Cut Line= 3
2280439.86394988637978.1285708812280476.25724544638286.303087457
2280511.70750259638637.378930692
#Sta/Elev= 30
       0 2212.56    19.2 2208.58    55.4 2202.66   111.1 2197.31   152.1 2194.66
   204.8 2193.04   237.2 2191.07   256.8 2191.16   280.4 2189.82   329.3 2188.62
   349.4 2184.56   361.5 2179.29   373.5 2175.82   425.8 2174.37   498.1 2174.32
   510.2 2172.16   522.3 2172.52   529.12170.554   534.3 2169.78   541.3 2170.52
   553.9 2171.35   582.6 2175.67   590.6 2178.54   610.7 2183.65   622.8 2189.82
   626.8    2191   642.9 2192.15   646.9 2193.64   654.9 2200.51   663.2 2204.17
#Mann= 5 ,-1,0
       0     .05       0     130     .06       0  330.32      .1       0
   529.1    .045       0   541.3     .06       0
Bank Sta=529.1,541.3
XS Rating Curve= 0 ,0
Exp/Cntr(USF)=0,0
Exp/Cntr=0.3,0.1

Type RM Length L Ch R = 1 ,8593    ,245.5,249.9,252.3
XS GIS Cut Line= 4
2280340.04154345638057.741800996 2280245.4637829638375.426073629
2280448.32661902638596.9506246112280457.47715839638639.821946358
#Sta/Elev= 30
       0 2201.45    45.3 2196.44    89.5 2193.04    99.1 2191.63   111.7 2191.89
   166.4 2187.88     229 2186.12   331.8 2181.72     371 2181.65   418.4  2180.5
   425.2 2180.95   430.9 2179.53   439.4 2175.21     4532165.451   459.9 2164.03
   469.4 2164.44   473.4 2165.37   480.3    2167   491.1 2166.45   507.2 2168.63
   523.7 2168.08   534.5 2169.97   539.9 2170.19   626.7 2170.31   632.1 2171.73
   636.2 2173.98   648.8 2184.12   660.7 2194.86   664.8 2197.41   675.7 2198.44
#Mann= 9 ,-1,0
       0     .06       0     260     .07       0     270     .05       0
  361.46     .07       0  371.46     .05       0     453    .045       0
   473.4     .05       0  501.46      .1       0  511.46     .06       0
#XS Ineff= 2 , 0
                          481.16         2168.25
Permanent Ineff=
       F       F
Bank Sta=453,473.4
XS Rating Curve= 0 ,0
Exp/Cntr(USF)=0,0
Exp/Cntr=0.3,0.1

Type RM Length L Ch R = 1 ,8343    ,201.2,202.5,203.3
XS GIS Cut Line= 2
2280054.46156919638180.3766985952280261.30313152638733.722074724
#Sta/Elev= 30
       0 2205.34    30.7 2204.76    43.6 2203.85    64.1 2199.42    85.9 2192.42
    98.3 2189.54   169.8 2180.73   278.6 2176.11   346.8 2175.61   363.8  2173.8
   370.5 2171.45   381.2 2166.15   389.5  2164.3   410.8 2163.32   419.3 2161.95
   436.4  2161.1   453.5 2161.85   468.2  2161.4   491.9 2162.75   504.8 2161.38
   513.3 2157.75   521.1 2156.55   527.3 2156.79   531.7 2157.75   543.2 2162.24
   547.5 2166.03   557.6 2176.63   573.1 2189.59   583.2 2196.76   590.7  2203.6
#Mann= 4 ,-1,0
       0     .05       0     450      .1       0   513.3    .045       0
   531.7      .1       0
Bank Sta=513.3,531.7
XS Rating Curve= 0 ,0
Exp/Cntr(USF)=0,0
Exp/Cntr=0.3,0.1

Type RM Length L Ch R = 1 ,8140    ,86.2,82.9,78.8
XS GIS Cut Line= 3
2279998.42205358638286.899771584 2280013.3592952638605.516772585
2280074.72389176638848.256460208
#Sta/Elev= 30
       0 2199.99    10.3 2197.12    26.3  2194.3    62.3 2184.48    74.4 2182.01
    84.2 2180.69   166.5 2173.41   250.6 2170.02   266.6 2168.97     282 2166.49
   310.6 2164.05   327.6  2161.4   359.9 2158.81   380.3 2158.03   388.8 2155.92
   421.8 2156.44   425.9    2155  429.56 2152.84   434.1 2152.35   442.9 2152.84
   450.6 2154.86   454.8 2155.06     463 2154.44   485.7 2154.18   500.2 2155.49
   508.4 2156.99   531.8 2158.84   537.3  2161.3   541.7 2164.07   569.3 2184.37
#Mann= 5 ,-1,0
       0     .05       0     220      .1       0  429.56    .045       0
   442.9      .1       0  548.97     .06       0
Bank Sta=429.56,442.9
XS Rating Curve= 0 ,0
Exp/Cntr(USF)=0,0
Exp/Cntr=0.3,0.1

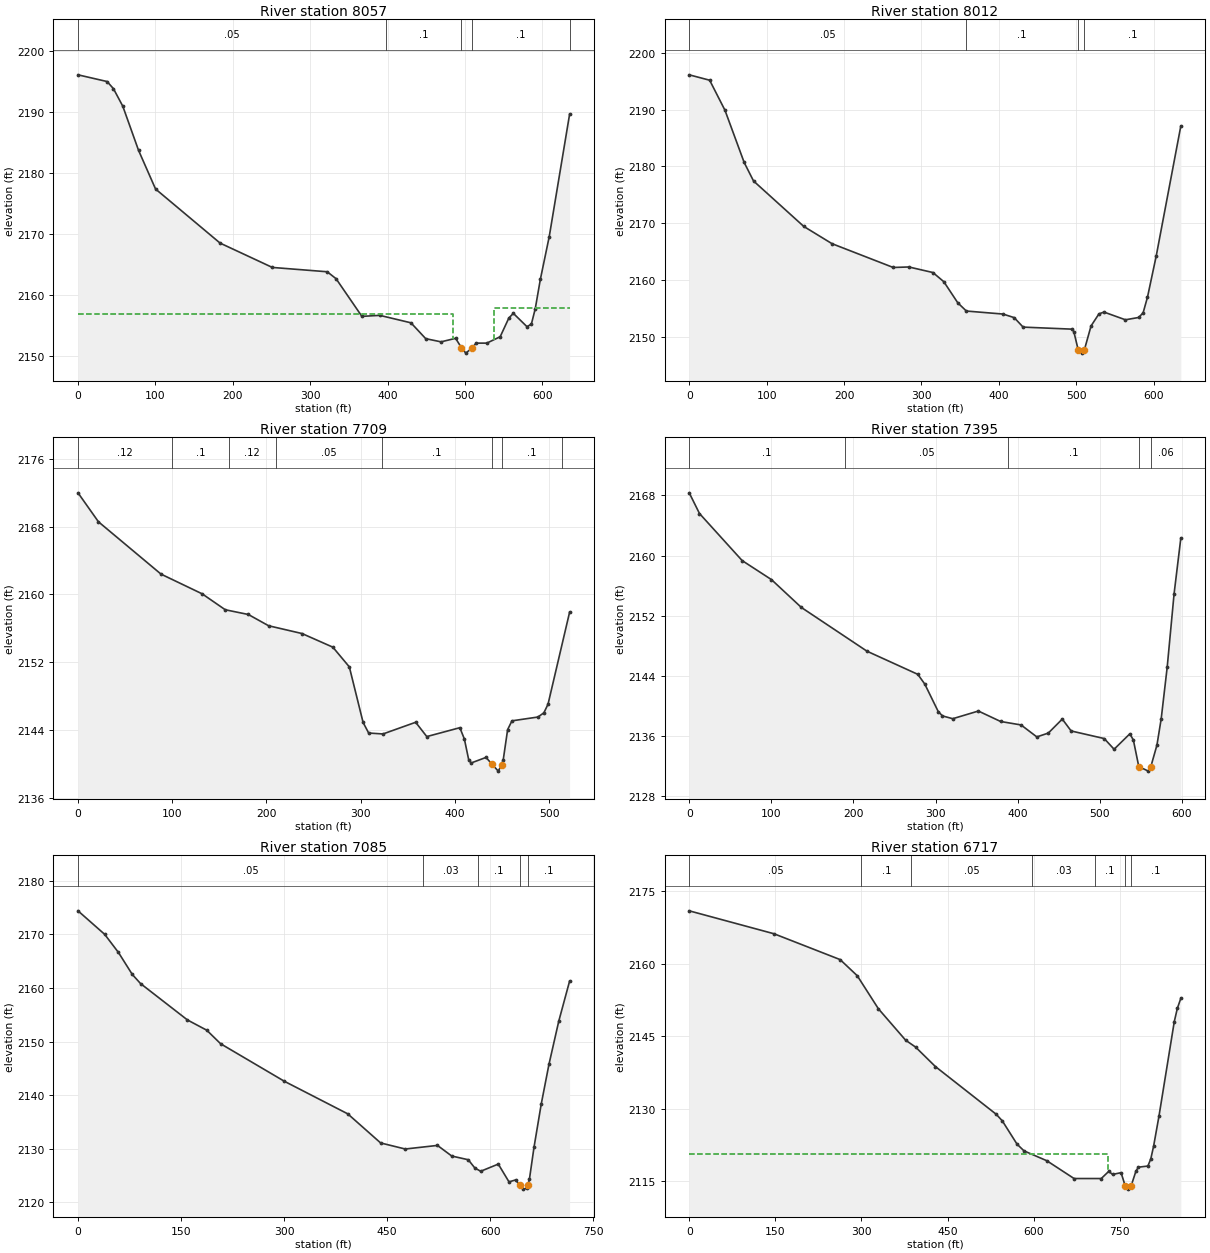
Type RM Length L Ch R = 1 ,8057    ,45.6,45.4,45.4
XS GIS Cut Line= 3
2279742.10572972638352.0288725842279779.23113835638576.549200918
2280072.69865412638859.409457086
#Sta/Elev= 30
       0 2196.03    37.6 2194.93    45.8 2193.76    57.9 2190.88    78.2 2183.66
   100.2 2177.31   183.6 2168.44   251.1 2164.45     322 2163.74   333.4 2162.61
   366.8 2156.43     390 2156.59   430.2 2155.37   449.3 2152.77   469.1 2152.25
   487.9 2152.83   495.5 2151.27   501.1  2150.4   509.42151.274   514.4 2152.04
   528.2 2152.04   545.5 2153.09   556.7 2156.16   562.5 2156.92   580.1 2154.74
   585.8 2155.16   590.8 2157.68   597.4  2162.5   608.9 2169.52   635.2 2189.58
#Mann= 5 ,-1,0
       0     .05       0  397.57      .1       0   495.5    .045       0
   509.4      .1       0  635.16     .06       0
#XS Ineff= 2 , 0
          483.95 2156.85  537.37         2157.79
Permanent Ineff=
       F       F
Bank Sta=495.5,509.4
XS Rating Curve= 0 ,0
Exp/Cntr(USF)=0,0
Exp/Cntr=0.3,0.1

Type RM Length L Ch R = 1 ,8012    ,303.8,302.8,300.5
XS GIS Cut Line= 3
2279709.07830418638383.172163376 2279746.2037128638607.692491709
2280039.67122858638890.552747877
#Sta/Elev= 30
       0 2196.13    26.4 2195.18    46.2 2189.89      71  2180.7    83.1 2177.44
     148 2169.44   184.5  2166.4   263.6 2162.21   283.8  2162.3   314.9 2161.32
     329  2159.7     347 2155.99   358.1 2154.54   405.4 2154.01   419.9 2153.38
   431.4 2151.71   494.9 2151.35     497 2150.89   502.5 2147.75   507.2 2147.13
  510.64 2147.74   519.2 2151.92   529.4 2154.04   535.9 2154.36   563.6    2153
   580.8 2153.41   586.5 2154.24   592.1 2156.98   603.4 2164.23   635.2 2187.13
#Mann= 4 ,-1,0
       0     .05       0  357.57      .1       0   502.5    .045       0
  510.64      .1       0
Bank Sta=502.5,510.64
XS Rating Curve= 0 ,0
Exp/Cntr(USF)=0,0
Exp/Cntr=0.3,0.1

Type RM Length L Ch R = 1 ,7709    ,310.6,314.3,316
XS GIS Cut Line= 4
2279545.91106119638595.874426939 2279600.9499871638872.946025827
2279785.30964707638976.7206012952279796.52213742639002.068119246
#Sta/Elev= 30
       0    2172    21.7 2168.58    88.1  2162.4   131.8 2160.07   156.3 2158.19
   180.8 2157.63   202.3  2156.3   237.8 2155.38   270.5 2153.77     288 2151.44
   302.6 2144.88   308.5 2143.63   323.7 2143.52   358.4  2144.9   370.2 2143.21
   405.3 2144.26   410.1 2142.92   414.7 2140.47   417.2 2140.09   433.1 2140.75
   439.42139.946   446.1 2139.13   449.72139.901   451.4  2140.5     456 2144.03
   460.6 2145.07   488.2 2145.52   494.5 2146.02   498.9 2147.04   521.8 2157.91
#Mann= 8 ,-1,0
       0     .12       0     100      .1       0     160     .12       0
     210     .05       0  322.49      .1       0   439.4    .045       0
   449.7      .1       0  514.05     .06       0
Bank Sta=439.4,449.7
XS Rating Curve= 0 ,0
Exp/Cntr(USF)=0,0
Exp/Cntr=0.3,0.1

Type RM Length L Ch R = 1 ,7395    ,309,310.3,310
XS GIS Cut Line= 3
2279383.82165566638704.711304266  2279394.131912638962.467712704
2279613.33567342639223.477250855
#Sta/Elev= 30
       0 2168.34    12.5 2165.59    64.5 2159.33   100.2  2156.8   136.6  2153.1
   216.6 2147.28   278.4 2144.21   286.9 2142.92   303.3 2139.26   308.5 2138.68
     321 2138.31   352.2 2139.33   379.3 2137.94   404.2 2137.48   423.4 2135.89
   437.4  2136.4   454.4 2138.26   465.2 2136.68   505.5 2135.67   517.5 2134.25
   536.7  2136.3     541 2135.47  547.58 2131.95   559.2 2131.34   562.3 2131.95
   569.7  2134.8   574.9 2138.31   582.2 2145.17   590.6 2154.94   598.8 2162.33
#Mann= 5 ,-1,0
       0      .1       0     190     .05       0  387.96      .1       0
  547.58    .045       0   562.3     .06       0
Bank Sta=547.58,562.3
XS Rating Curve= 0 ,0
Exp/Cntr(USF)=0,0
Exp/Cntr=0.3,0.1

Type RM Length L Ch R = 1 ,7085    ,365.6,367.6,369.4
XS GIS Cut Line= 3
2279231.25930224638702.5101478562279191.97315555639143.388016266
2279366.57825195639352.914131946
#Sta/Elev= 30
       0 2174.37    38.8 2169.99    58.9  2166.6      79 2162.51      91 2160.81
   159.3 2154.02   187.4 2152.11   207.5 2149.59   300.3 2142.59   392.5 2136.52
   440.4 2131.09   476.2 2129.96   523.1 2130.63   543.9 2128.65   567.9 2127.96
   577.5 2126.42     586 2125.81   611.6 2127.15   627.2 2123.83   637.2 2124.21
   642.5 2123.18     648 2122.48   653.2 2122.63   654.82123.161     657 2124.41
   663.6 2130.29   674.1 2138.34   685.4 2145.78   699.6 2153.79   715.4 2161.28
#Mann= 5 ,-1,0
       0     .05       0  502.62     .03       0  582.62      .1       0
   642.5    .045       0   654.8      .1       0
Bank Sta=642.5,654.8
XS Rating Curve= 0 ,0
Exp/Cntr(USF)=0,0
Exp/Cntr=0.3,0.1

Type RM Length L Ch R = 1 ,6717    ,150.6,151.9,153.4
XS GIS Cut Line= 3
2279050.10651472638770.1696227112278847.12809016639075.728541411
2279030.46344138639529.701792051
#Sta/Elev= 30
       0  2170.9   147.7 2166.16   262.9 2160.82   292.7 2157.49   329.6 2150.65
     377 2144.16   394.3 2142.74   428.8 2138.72   534.7 2128.86   545.3 2127.51
   571.1 2122.67   583.3 2121.28   622.9 2119.25   670.4 2115.57   717.8 2115.57
   730.8 2117.05   737.5 2116.42   752.3 2116.78  759.67 2113.99   765.2 2113.38
   769.6 2113.97   778.2  2117.1   782.5 2117.92     799 2118.15   804.1 2119.64
     809 2122.28   818.3 2128.45     845 2148.01   850.3 2150.73   856.4 2152.82
#Mann= 7 ,-1,0
       0     .05       0     300      .1       0  386.83     .05       0
  596.83     .03       0  706.83      .1       0  759.67    .045       0
   769.6      .1       0
#XS Ineff= 2 , 0
          729.24 2120.56
Permanent Ineff=
       F       F
Bank Sta=759.67,769.6
XS Rating Curve= 0 ,0
Exp/Cntr(USF)=0,0
Exp/Cntr=0.3,0.1

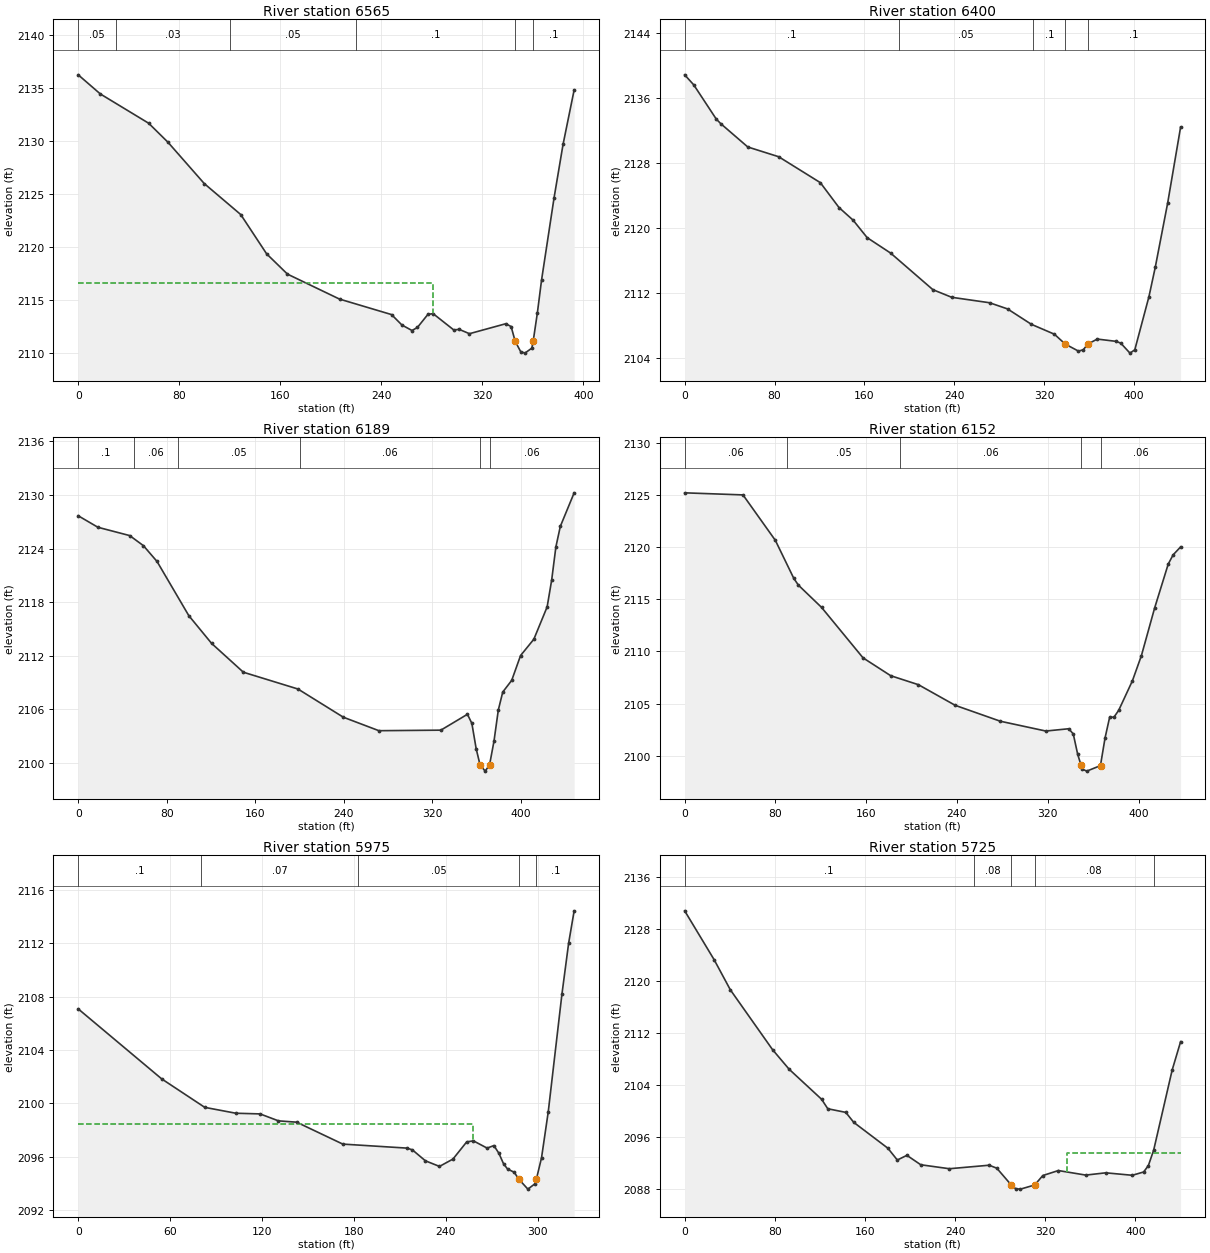
Type RM Length L Ch R = 1 ,6565    ,166.2,165.2,164.2
XS GIS Cut Line= 2
2278781.71811389639176.1974699422278874.85957696 639557.74081265
#Sta/Elev= 30
       0 2136.22    17.5 2134.42    55.8 2131.66      71 2129.88    99.8 2125.98
   128.7 2123.06   149.2 2119.36   165.7 2117.45   206.9  2115.1   248.1 2113.64
   256.3 2112.66   264.3 2112.14   268.6 2112.43   276.9 2113.66     281 2113.73
   297.4 2112.19   301.6 2112.25   309.8 2111.84   338.6 2112.78   342.8 2112.51
     3462111.129   350.3 2110.16   353.7 2110.01   359.2 2110.48   360.3 2111.16
   363.6 2113.82   366.9  2116.9   376.8 2124.64   383.9 2129.66   392.7  2134.8
#Mann= 6 ,-1,0
       0     .05       0      30     .03       0     120     .05       0
     220      .1       0     346    .045       0   360.3      .1       0
#XS Ineff= 2 , 0
          280.84 2116.63
Permanent Ineff=
       F       F
Bank Sta=346,360.3
XS Rating Curve= 0 ,0
Exp/Cntr(USF)=0,0
Exp/Cntr=0.3,0.1

Type RM Length L Ch R = 1 ,6400    ,212.1,211.2,209.6
XS GIS Cut Line= 3
2278627.26797268639201.0697661722278633.08288365639311.505295876
2278729.37674189639628.246597909
#Sta/Elev= 30
       0 2138.88     8.1 2137.64    28.1 2133.44    32.2 2132.86    56.2    2130
    83.7  2128.8   120.8 2125.61   137.4 2122.55     150 2120.99   162.5 2118.84
   183.4 2116.94     221 2112.44   237.8  2111.5   271.5 2110.83   287.5 2110.07
   308.8 2108.17   329.2 2106.96   338.8 2105.75   350.6 2104.88   354.9 2105.04
     359 2105.75   367.4 2106.36   384.1 2106.08   388.3 2105.86   396.5 2104.63
   400.8 2105.04   413.4 2111.58     419 2115.18   430.1 2123.13   441.6 2132.46
#Mann= 5 ,-1,0
       0      .1       0  190.59     .05       0  310.59      .1       0
   338.8    .045       0     359      .1       0
Bank Sta=338.8,359
XS Rating Curve= 0 ,0
Exp/Cntr(USF)=0,0
Exp/Cntr=0.3,0.1

Type RM Length L Ch R = 1 ,6189    ,36.4,36.2,36.2
XS GIS Cut Line= 3
2278602.54675506639295.8465940632278548.17000395639529.098911572
 2278548.2527796639737.563780227
#Sta/Elev= 30
       0 2127.67    17.8 2126.38    46.5 2125.45    58.9 2124.32    71.2 2122.55
    99.9 2116.48   120.5 2113.37   149.2 2110.14   198.5 2108.26   239.5  2105.1
   271.6 2103.59   327.6 2103.65   351.6 2105.43   355.6 2104.41   359.5 2101.56
  362.97 2099.77   367.6 2099.06   371.6 2099.75   371.6 2099.77   375.6 2102.43
   379.5 2105.91   383.5 2107.92   391.6 2109.23   399.6 2112.01   411.6 2113.84
   423.6 2117.46   427.7 2120.47   431.5 2124.18   435.5 2126.48     448 2130.24
#Mann= 6 ,-1,0
       0      .1       0      50     .06       0      90     .05       0
     200     .06       0  362.97    .045       0   371.6     .06       0
Bank Sta=362.97,371.6
XS Rating Curve= 0 ,0
Exp/Cntr(USF)=0,0
Exp/Cntr=0.3,0.1

Type RM Length L Ch R = 1 ,6152    ,183.3,177.2,173.6
XS GIS Cut Line= 3
2278554.22935013639302.6320315152278511.77361586639531.566447017
2278512.47281197   639735.856115
#Sta/Elev= 30
       0 2125.19    51.4 2124.99    79.9 2120.64    96.2 2116.99   100.2 2116.35
   120.6 2114.22   157.2 2109.38   181.6 2107.67     206 2106.81   238.5 2104.83
   278.2 2103.31   318.3 2102.37   338.5 2102.59   342.5 2102.09   346.4 2100.13
  349.41 2099.08   350.4 2098.72   354.4 2098.53   366.5 2099.06   366.5  2099.1
   370.5 2101.71   374.5 2103.67   378.4 2103.71   382.5 2104.35   394.6 2107.18
   402.5 2109.58   414.2 2114.16   426.2 2118.37   430.5 2119.25   437.1 2120.01
#Mann= 5 ,-1,0
       0     .06       0      90     .05       0     190     .06       0
  349.41    .045       0   366.5     .06       0
Bank Sta=349.41,366.5
XS Rating Curve= 0 ,0
Exp/Cntr(USF)=0,0
Exp/Cntr=0.3,0.1

Type RM Length L Ch R = 1 ,5975    ,249.2,250,249
XS GIS Cut Line= 3
 2278300.4591318639506.9666385952278310.93827955639609.292434218
2278406.48345016639808.396241363
#Sta/Elev= 30
       0 2107.08    54.5 2101.84    82.6 2099.71   102.9 2099.27   118.7 2099.22
   130.7  2098.7   142.6  2098.6   172.7 2096.96   214.6 2096.66   218.1 2096.53
   226.6 2095.71   235.8 2095.29   244.6 2095.84   253.6 2097.13     258  2097.2
   266.9 2096.66   271.3 2096.85   274.6 2096.27   277.6 2095.49   280.2  2095.1
   284.6 2094.85   287.6 2094.33   293.5 2093.59     298 2093.98   299.12094.362
   302.4 2095.93   306.8 2099.38   315.7 2108.16   320.1    2112   323.7 2114.42
#Mann= 5 ,-1,0
       0      .1       0      80     .07       0  182.86     .05       0
   287.6    .045       0   299.1      .1       0
#XS Ineff= 2 , 0
          257.41 2098.45
Permanent Ineff=
       F       F
Bank Sta=287.6,299.1
XS Rating Curve= 0 ,0
Exp/Cntr(USF)=0,0
Exp/Cntr=0.3,0.1

Type RM Length L Ch R = 1 ,5725    ,410.2,409.2,397.6
XS GIS Cut Line= 4
2278032.68548584 639552.440741132278119.64865172639682.548244528
2278199.64622995639929.5843343412278217.83816742639945.116234899
#Sta/Elev= 30
       0 2130.78    26.1 2123.27    40.5 2118.63      78 2109.41    92.7  2106.4
   121.5 2101.78     127 2100.32     143 2099.76     150 2098.23   180.3 2094.25
   188.7 2092.43   197.2 2093.15   209.5  2091.7   234.9 2091.09   270.2 2091.63
     277 2091.17   289.6 2088.63   293.8    2088     298 2087.95   310.6 2088.59
   317.8 2090.04   331.6 2090.81   355.9 2090.11   373.7 2090.46   397.2 2090.08
   407.3 2090.59   411.5 2091.58   416.2 2093.96   432.6 2106.28   440.1 2110.65
#Mann= 5 ,-1,0
       0      .1       0  256.49     .08       0   289.6    .045       0
   310.6     .08       0  416.16      .1       0
#XS Ineff= 2 , 0
                          339.35         2093.58
Permanent Ineff=
       F       F
Bank Sta=289.6,310.6
XS Rating Curve= 0 ,0
Exp/Cntr(USF)=0,0
Exp/Cntr=0.3,0.1

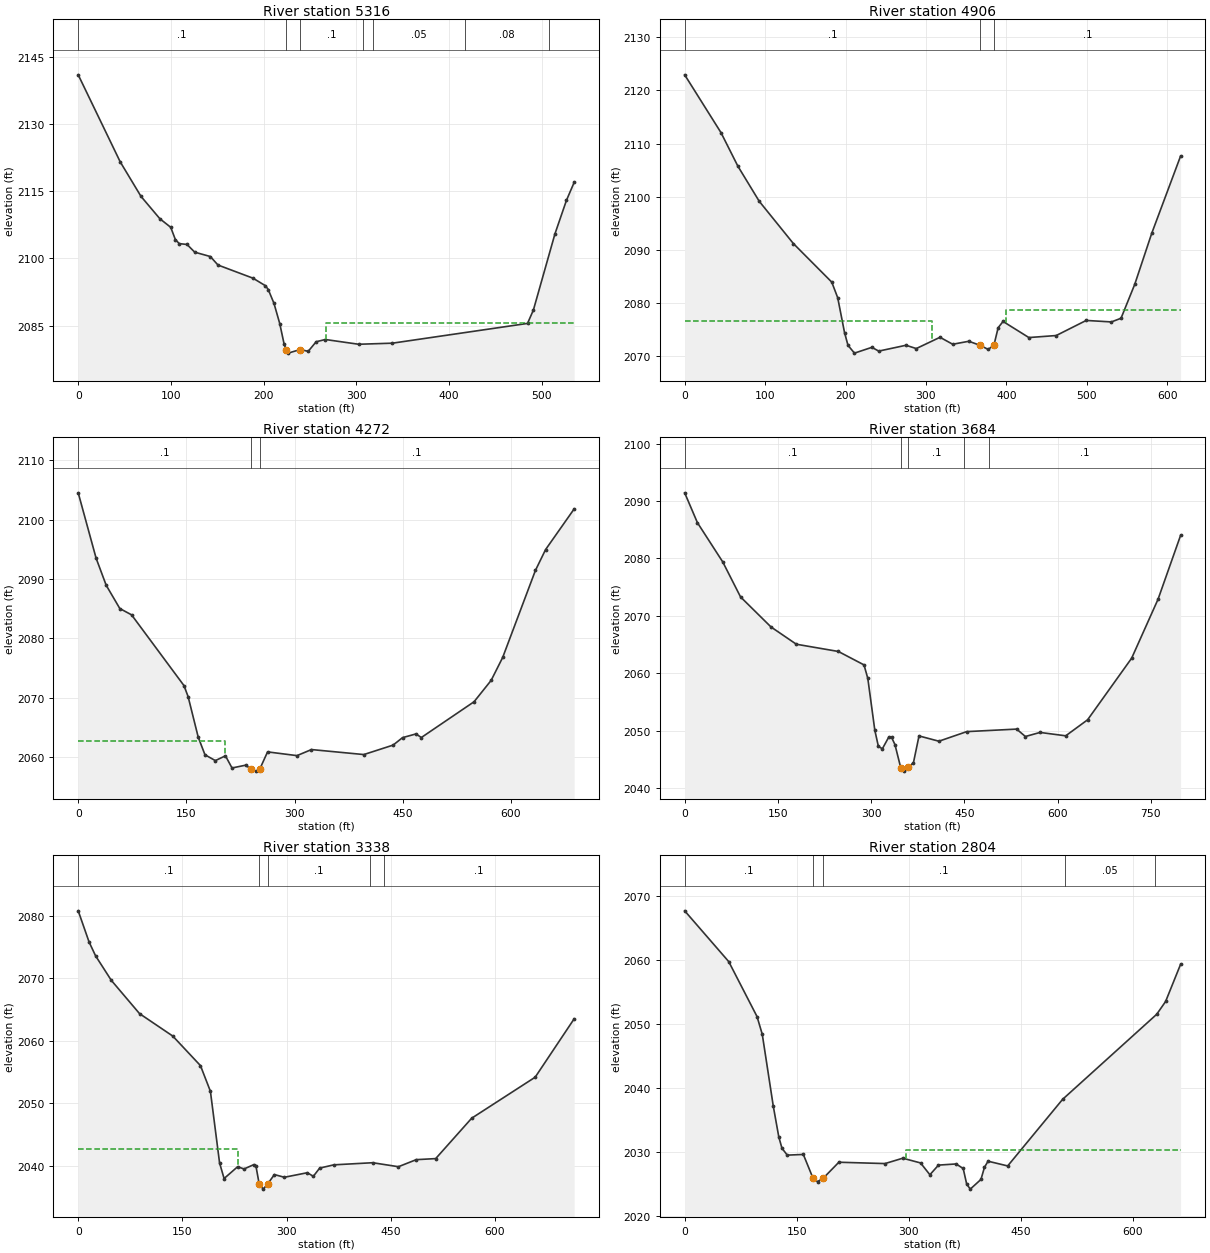
Type RM Length L Ch R = 1 ,5316    ,408.9,410.1,406.2
XS GIS Cut Line= 4
2277748.00384592639740.8611336972277803.67923014639924.125940093
2277874.25010165639952.3070256272278103.22239493 640090.47184132
#Sta/Elev= 30
       0 2140.99    45.3 2121.57    67.7 2113.87    88.1 2108.87    99.8 2106.96
   104.8 2104.23     109 2103.32   117.4 2103.13   125.7 2101.41   142.5 2100.44
   150.8 2098.54   188.5 2095.61     202 2093.92     205 2093.08   211.2 2089.98
   217.4 2085.48   222.2 2080.82  224.35 2079.68   226.5 2078.88   239.4 2079.68
   248.1 2079.28   256.7 2081.42   266.6 2081.92   302.5 2080.86   338.9  2081.1
   484.7 2085.51     491 2088.48   514.3 2105.51   526.7 2112.98     535 2116.98
#Mann= 7 ,-1,0
       0      .1       0  224.35    .045       0   239.4      .1       0
  307.52     .08       0  317.52     .05       0  417.52     .08       0
  507.52      .1       0
#XS Ineff= 2 , 0
                          266.93         2085.68
Permanent Ineff=
       F       F
Bank Sta=224.35,239.4
XS Rating Curve= 0 ,0
Exp/Cntr(USF)=0,0
Exp/Cntr=0.3,0.1

Type RM Length L Ch R = 1 ,4906    ,630.5,633.9,635.6
XS GIS Cut Line= 2
2277364.79067525640127.0370684452277946.03137627640333.242195192
#Sta/Elev= 30
       0 2122.94    45.1 2112.08    66.2 2105.74    92.7 2099.15   135.2 2091.19
   182.9 2083.94   190.3    2081   198.8 2074.43   203.1 2072.04   211.1 2070.58
   232.8 2071.67   241.3 2070.96   275.2 2072.06     288 2071.44   317.5 2073.56
   333.3 2072.25   353.3 2072.81   367.7 2072.03   377.3 2071.28   384.52072.045
   389.8 2075.36   395.9 2076.54     428 2073.51     462 2073.89   499.3 2076.73
   530.6 2076.45   542.6 2077.14   559.6  2083.5   580.8 2093.13   616.7 2107.67
#Mann= 3 ,-1,0
       0      .1       0   367.7    .045       0   384.5      .1       0
#XS Ineff= 2 , 0
           307.8 2076.66  399.78          2078.7
Permanent Ineff=
       F       F
Bank Sta=367.7,384.5
XS Rating Curve= 0 ,0
Exp/Cntr(USF)=0,0
Exp/Cntr=0.3,0.1

Type RM Length L Ch R = 1 ,4272    ,583.7,587.9,587.3
XS GIS Cut Line= 2
2277199.31290021640483.965131467 2277781.6514526640849.915587886
#Sta/Elev= 30
       0 2104.52    24.8 2093.52    38.8 2088.96    57.7 2085.04      74 2083.98
   146.6 2072.08   152.4 2070.22   166.4  2063.4   175.8 2060.42   190.2 2059.44
   204.2 2060.25   213.3  2058.2   232.5 2058.68   239.4 2057.98   246.7 2057.67
  251.722057.991   262.6 2060.91   303.4 2060.28   323.5  2061.3   396.1 2060.46
   436.7 2062.05   449.8 2063.31   468.4 2063.93   475.9 2063.33     549 2069.35
   572.7 2072.95   588.7 2076.81   634.1 2091.46   648.2 2094.97   687.8 2101.81
#Mann= 3 ,-1,0
       0      .1       0   239.4    .045       0  251.72      .1       0
#XS Ineff= 2 , 0
          203.18 2062.69
Permanent Ineff=
       F       F
Bank Sta=239.4,251.72
XS Rating Curve= 0 ,0
Exp/Cntr(USF)=0,0
Exp/Cntr=0.3,0.1

Type RM Length L Ch R = 1 ,3684    ,344.2,346,346.3
XS GIS Cut Line= 3
2276994.52719165640665.0990519322277034.62263296640861.280318351
2277474.24050734641266.530671611
#Sta/Elev= 30
       0 2091.43    20.5 2086.23    61.3 2079.39    89.9  2073.3   138.9 2068.07
   179.7 2065.06   247.3  2063.8   288.6 2061.46   294.7 2059.11     306 2050.07
   311.7 2047.28   318.1 2046.85   328.6 2048.92   332.9 2048.85   338.4 2047.58
   347.6 2043.59   353.5 2042.96   360.1  2043.6   368.2 2044.45   377.1 2049.09
   409.1 2048.17   453.9 2049.84   534.2 2050.28   548.3 2048.99   571.9  2049.7
   613.2 2049.11   648.4  2051.9   719.3 2062.63   761.8  2072.9   798.1 2084.03
#Mann= 5 ,-1,0
       0      .1       0   347.6    .045       0   360.1      .1       0
  450.24     .05       0  490.24      .1       0
Bank Sta=347.6,360.1
XS Rating Curve= 0 ,0
Exp/Cntr(USF)=0,0
Exp/Cntr=0.3,0.1

Type RM Length L Ch R = 1 ,3338    ,534.4,533.8,530
XS GIS Cut Line= 2
2276758.52003053641011.6940969022277199.25166718641573.348493057
#Sta/Elev= 30
       0 2080.82    15.6 2075.84      25 2073.61    47.6 2069.69    88.3 2064.35
   136.1 2060.76     176 2056.02   190.3 2051.91   203.5 2040.43     210 2037.94
   229.5 2039.83   238.7 2039.47   252.9 2040.17   255.8 2039.96   260.52037.079
   266.3 2036.24   272.9  2037.1   282.4 2038.57   296.8 2038.14   329.9 2038.87
   338.4 2038.29   347.6 2039.61     368 2040.13   423.9 2040.47   460.9 2039.83
   486.6 2040.96   514.6 2041.13   566.4  2047.6   657.8 2054.17   713.9 2063.52
#Mann= 5 ,-1,0
       0      .1       0   260.5    .045       0   272.9      .1       0
     420     .05       0     440      .1       0
#XS Ineff= 2 , 0
          229.89  2042.6
Permanent Ineff=
       F       F
Bank Sta=260.5,272.9
XS Rating Curve= 0 ,0
Exp/Cntr(USF)=0,0
Exp/Cntr=0.3,0.1

Type RM Length L Ch R = 1 ,2804    ,138.5,136.7,130.7
XS GIS Cut Line= 2
2276394.58238286 641468.909667182276953.05460114641828.495767835
#Sta/Elev= 30
       0 2067.72      59 2059.77    96.9 2051.17   103.9  2048.4   118.7 2037.12
   126.1  2032.3   130.3 2030.56   137.4 2029.48   158.9 2029.59     1722025.831
   177.9 2025.34   185.2 2025.83   206.5 2028.37   268.3 2028.16   292.1    2029
   315.9 2028.26   328.4 2026.41   339.9 2027.92   363.5  2028.1     373 2027.39
   377.7 2024.95   382.5 2024.16   396.8 2025.68   401.5 2027.58   406.3 2028.53
   432.6 2027.79   506.2 2038.22   632.2 2051.53   644.1 2053.53   664.2 2059.36
#Mann= 5 ,-1,0
       0      .1       0     172    .045       0   185.2      .1       0
     510     .05       0     630      .1       0
#XS Ineff= 2 , 0
                          296.68         2030.21
Permanent Ineff=
       F       F
Bank Sta=172,185.2
XS Rating Curve= 0 ,0
Exp/Cntr(USF)=0,0
Exp/Cntr=0.3,0.1