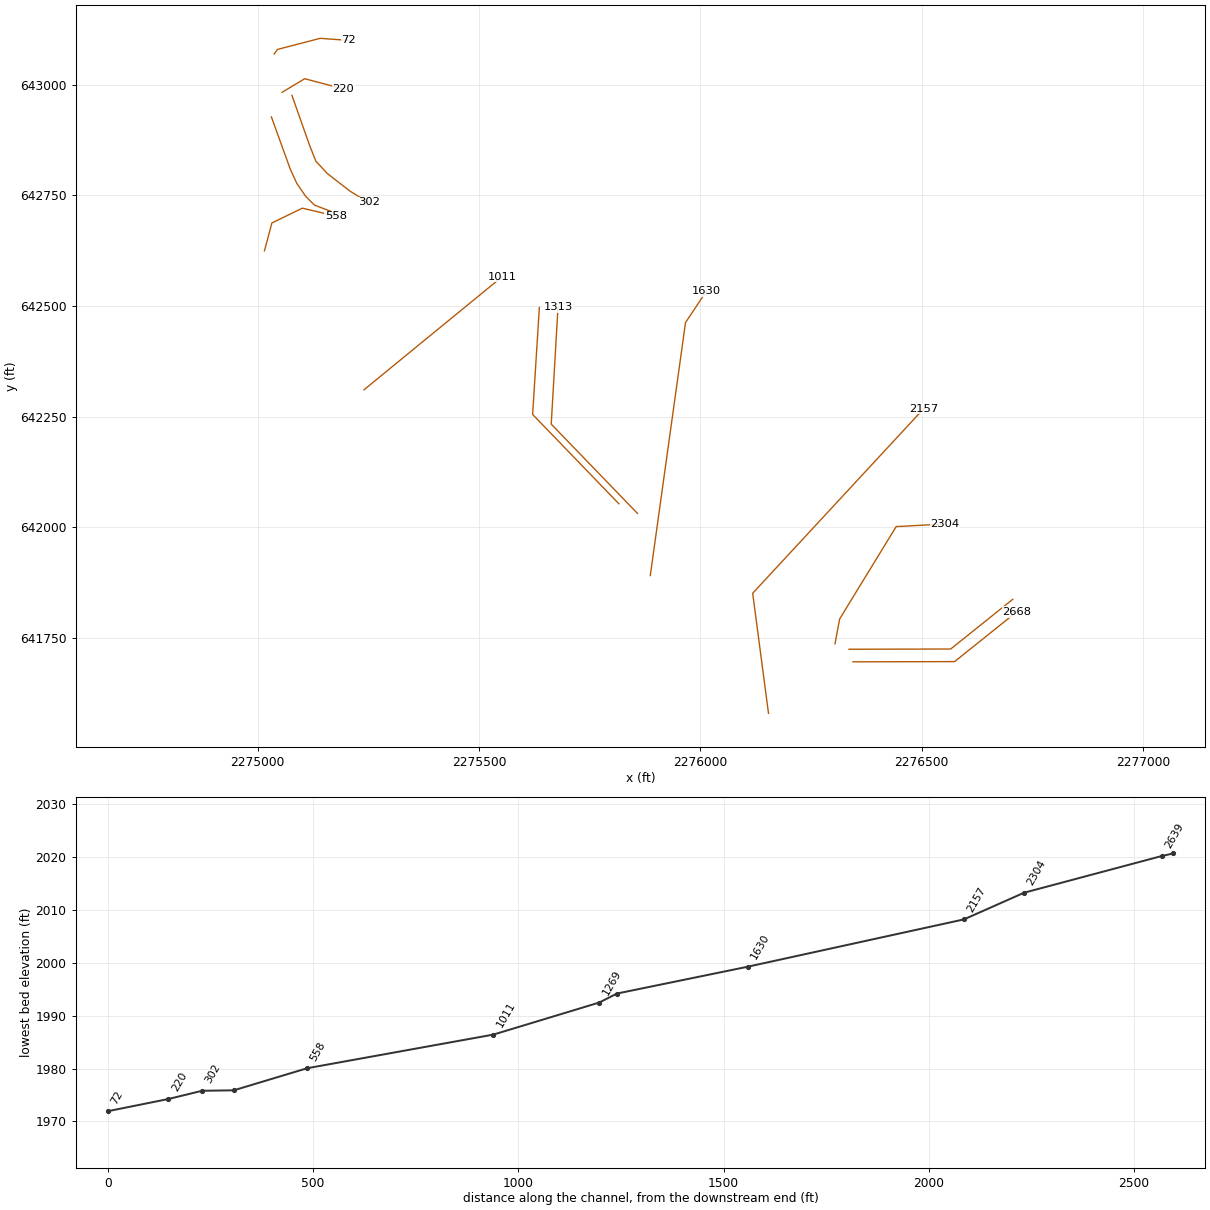
HEC-RAS study CRWFRDRN.prj: CRWFRDRN

--- CRWFRDRN.g01 (geometry) --- (continued)

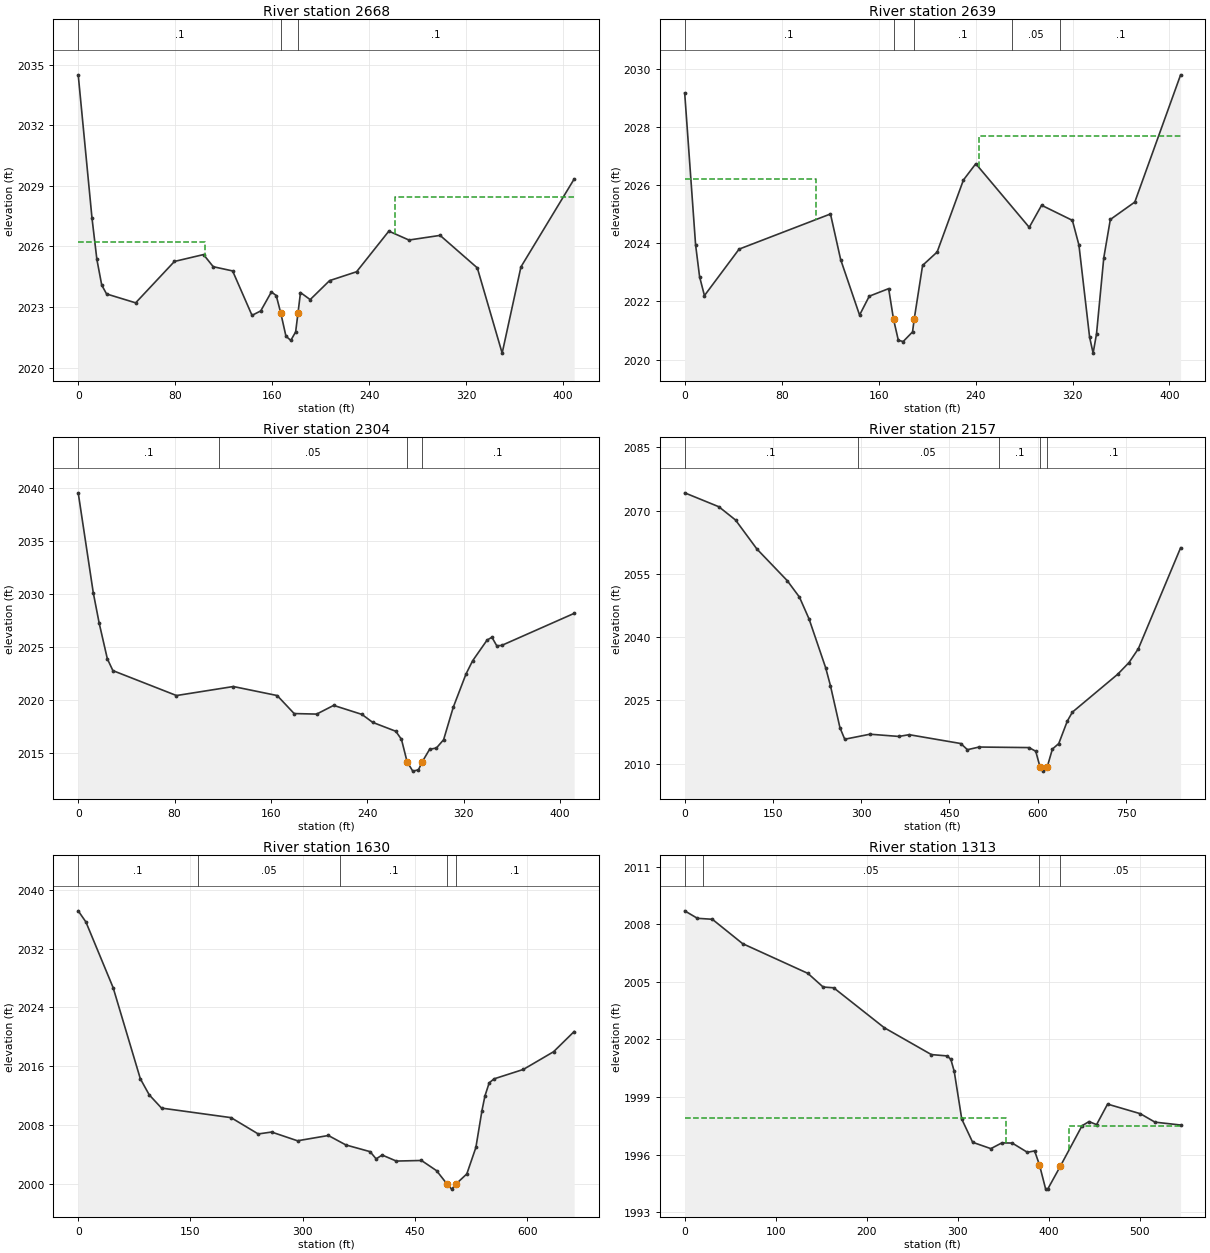
Type RM Length L Ch R = 1 ,2668    ,28.7,28.8,28.5
XS GIS Cut Line= 3
2276344.72646879641696.0055308192276574.45043102641696.542269048
2276714.53910892641808.720559014
#Sta/Elev= 30
       0  2034.5    11.4 2027.39    15.4 2025.36    19.4 2024.09    23.4 2023.65
    47.4 2023.21    79.4 2025.26   103.4  2025.6   111.4    2025   127.4 2024.79
   143.4 2022.59   150.6 2022.81   159.4 2023.75   163.4 2023.57   167.22022.686
   171.4 2021.56   175.4 2021.35   179.4 2021.77   181.32022.683   183.4 2023.72
   191.4 2023.37   207.4 2024.31   229.7 2024.75   256.3 2026.76   272.9 2026.32
   298.6 2026.55   329.3 2024.94   349.8 2020.72   365.3 2024.99   409.2 2029.34
#Mann= 3 ,-1,0
       0      .1       0   167.2    .045       0   181.3      .1       0
#XS Ineff= 2 , 0
          104.86 2026.21  261.16         2028.46
Permanent Ineff=
       F       F
Bank Sta=167.2,181.3
XS Rating Curve= 0 ,0
Exp/Cntr(USF)=0,0
Exp/Cntr=0.3,0.1

Type RM Length L Ch R = 1 ,2639    ,329.7,335,342.7
XS GIS Cut Line= 3
  2276335.870288641724.4526569822276565.59425023641724.989395212
2276705.68292813641837.167685177
#Sta/Elev= 30
       0 2029.18       9 2023.95    12.3 2022.85    16.3  2022.2    44.9  2023.8
   120.3 2025.01   128.7 2023.44   144.3 2021.53   152.3 2022.18   168.3 2022.44
   172.3 2021.39   176.3 2020.66   180.3 2020.62     188 2020.95   189.42021.394
   196.3 2023.24   208.3  2023.7     230 2026.18   240.2 2026.74   284.3 2024.55
   294.5 2025.31   319.9 2024.79   325.3 2023.94   334.1 2020.77     337 2020.22
   339.8 2020.88   345.8  2023.5   351.2 2024.82   371.4 2025.42   409.2  2029.8
#Mann= 5 ,-1,0
       0      .1       0   172.3    .045       0   189.4      .1       0
  269.72     .05       0  309.72      .1       0
#XS Ineff= 2 , 0
          107.97 2026.21  242.79          2027.7
Permanent Ineff=
       F       F
Bank Sta=172.3,189.4
XS Rating Curve= 0 ,0
Exp/Cntr(USF)=0,0
Exp/Cntr=0.3,0.1

Type RM Length L Ch R = 1 ,2304    ,146.3,146.6,143.7
XS GIS Cut Line= 4
2276304.23815506641736.8436597132276314.71838478641792.941687204
2276442.41726901642001.5549576242276552.41547407642007.518715729
#Sta/Elev= 30
       0 2039.53    12.5 2030.11    17.4 2027.24    24.2 2023.87    28.8 2022.76
    81.6 2020.41   128.8 2021.26   165.2 2020.41   179.3 2018.71     198 2018.66
   212.1 2019.48   235.6 2018.63   244.5 2017.88   263.7 2017.04   268.4 2016.28
   273.1 2014.16   277.8 2013.28   282.5  2013.4   285.72014.171   291.8 2015.34
   297.4 2015.46   303.4 2016.24   311.4  2019.3     322 2022.44   327.5 2023.69
   339.5 2025.64   343.5 2025.91   347.5 2025.11   351.5 2025.13   411.8 2028.16
#Mann= 4 ,-1,0
       0      .1       0  117.07     .05       0   273.1    .045       0
   285.7      .1       0
Bank Sta=273.1,285.7
XS Rating Curve= 0 ,0
Exp/Cntr(USF)=0,0
Exp/Cntr=0.3,0.1

Type RM Length L Ch R = 1 ,2157    ,522.1,526.9,529.8
XS GIS Cut Line= 3
2276153.95036926641579.5525516422276118.22005536641850.999745685
2276504.98671311 642268.39148258
#Sta/Elev= 30
       0 2074.19    58.1 2070.89    86.4 2067.75   122.7 2060.88   174.2 2053.39
     195 2049.48   211.4 2044.29   239.7 2032.68   247.7 2028.49   263.9 2018.51
     272 2015.79   314.9 2016.98     364 2016.45   381.4 2016.87   469.2 2014.77
   480.5 2013.31   500.3 2013.94   585.2 2013.81   596.6 2012.94     604 2009.15
   609.4 2008.23  616.012009.187   624.9 2013.46   635.7 2014.76   650.3 2020.11
   658.8  2022.2   735.7 2031.17   755.1 2033.96     771 2037.25   842.8 2061.17
#Mann= 5 ,-1,0
       0      .1       0  293.79     .05       0  533.79      .1       0
     604    .045       0  616.01      .1       0
Bank Sta=604,616.01
XS Rating Curve= 0 ,0
Exp/Cntr(USF)=0,0
Exp/Cntr=0.3,0.1

Type RM Length L Ch R = 1 ,1630    ,317.5,317.9,316.7
XS GIS Cut Line= 3
2275886.84102058641890.9336772832275966.45384955  642462.6419731
2276013.80576383642533.669844521
#Sta/Elev= 30
       0 2037.15    10.3 2035.63    46.7 2026.68      83 2014.29    94.9  2012.1
   111.3  2010.3   204.2    2009   240.5 2006.78   258.4 2007.04     293 2005.85
   334.2 2006.57   357.7 2005.28     390 2004.37     398 2003.39   406.1 2003.91
     425 2003.09   458.6 2003.17   478.8 2001.78   492.4 2000.01     499 1999.27
   505.22000.012   519.2 2001.34   531.3 2004.94   539.4 2009.94   543.4 2011.95
   549.1 2013.74   555.6 2014.28   594.7 2015.56   635.1 2017.97   662.6 2020.72
#Mann= 5 ,-1,0
       0      .1       0     160     .05       0     350      .1       0
   492.4    .045       0   505.2      .1       0
Bank Sta=492.4,505.2
XS Rating Curve= 0 ,0
Exp/Cntr(USF)=0,0
Exp/Cntr=0.3,0.1

Type RM Length L Ch R = 1 ,1313    ,43.5,43.1,42.9
XS GIS Cut Line= 3
2275857.88246625642031.3434907812275663.01862147642233.166758591
2275678.33946574642497.411291141
#Sta/Elev= 30
       0  2008.7      14 2008.31    30.4 2008.26    63.7 2006.99   135.5 2005.44
   152.2 2004.73   163.8 2004.69   219.4 2002.61   271.2 2001.21   288.6 2001.14
   292.6 2000.96   296.3 2000.34   304.6 1997.85   316.6 1996.64   336.6 1996.31
   348.7 1996.61   360.1  1996.6   376.7 1996.12   384.7 1996.19389.99991995.468
   396.8 1994.21   399.1  1994.2   412.8 1995.38   436.8  1997.5   444.5 1997.72
   452.8 1997.56   464.9 1998.63   500.9 1998.13     517 1997.69   545.2 1997.54
#Mann= 4 ,-1,0
       0      .1       0      20     .05       0389.9999    .045       0
   412.8     .05       0
#XS Ineff= 2 , 0
           353.5 1997.88  422.38          1997.5
Permanent Ineff=
       F       F
Bank Sta=389.9999,412.8
XS Rating Curve= 0 ,0
Exp/Cntr(USF)=0,0
Exp/Cntr=0.3,0.1

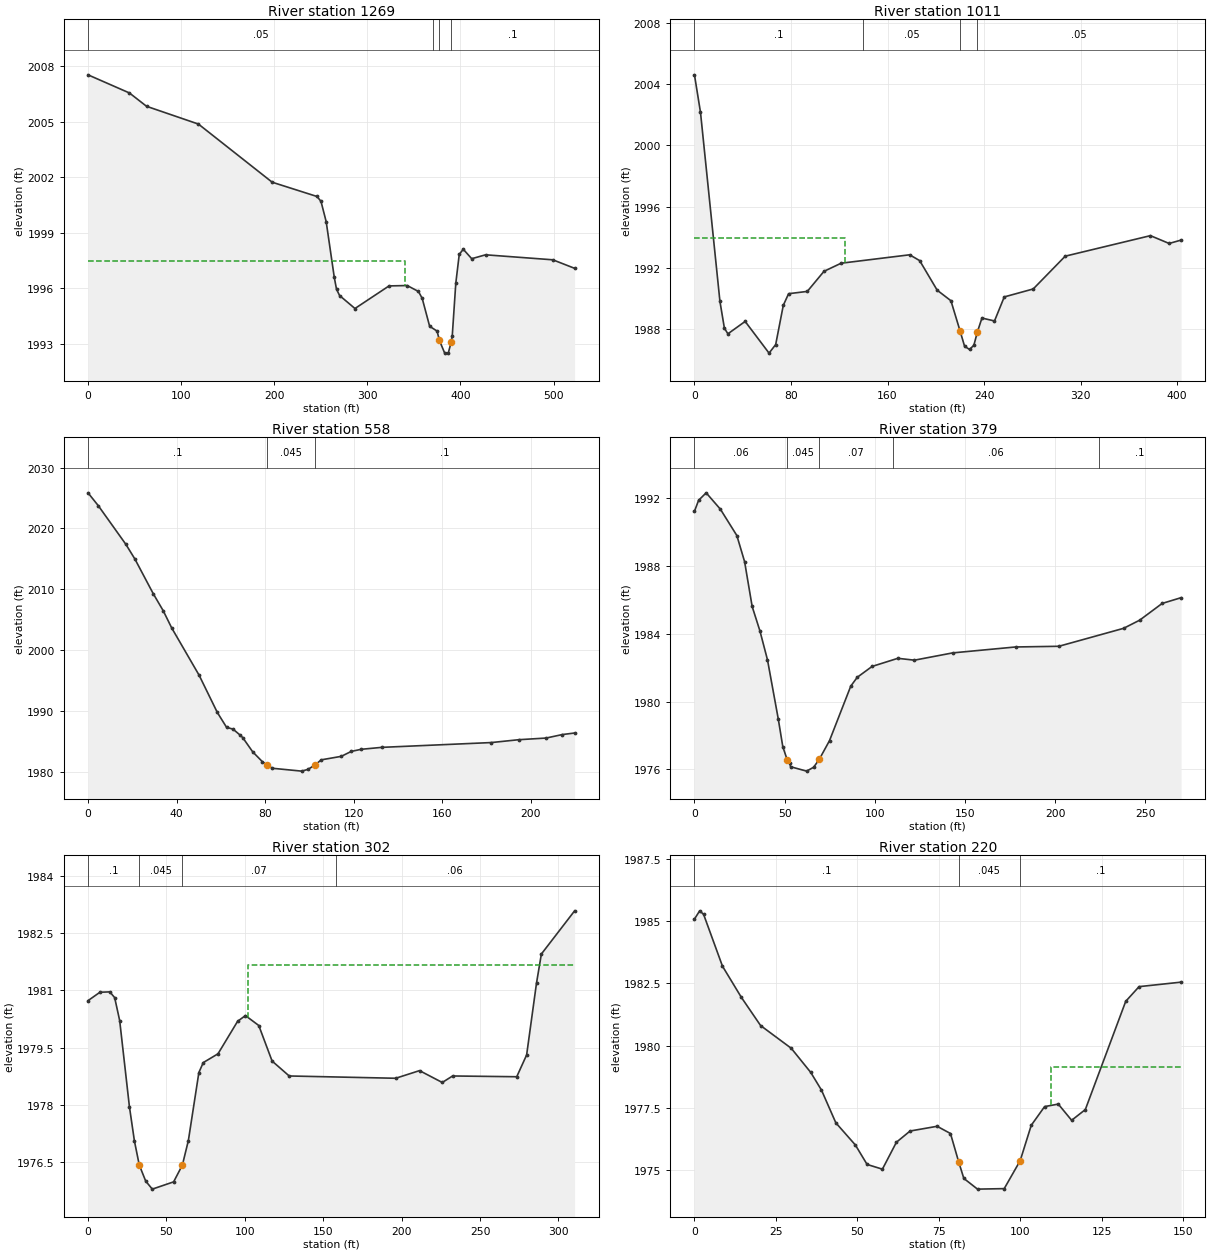
Type RM Length L Ch R = 1 ,1269    ,263.4,258,252.2
XS GIS Cut Line= 3
2275815.86085526642053.1717443062275620.99701048642254.995012116
 2275636.1756088642496.615746671
#Sta/Elev= 30
       0 2007.53    44.5 2006.55    62.9 2005.83   118.6 2004.87   197.8 2001.73
   245.9 2000.96   250.2  2000.7   255.8  1999.6   264.5 1996.59   266.9 1995.95
   270.2 1995.61   286.7 1994.91   323.3 1996.13   342.8 1996.15   354.9 1995.83
   358.9 1995.46   366.9 1993.95   374.9 1993.69   377.41993.185   382.9 1992.52
   386.9  1992.5390.19921993.123   391.2 1993.44     395 1996.28   398.7 1997.83
     403 1998.11   412.1  1997.6     427 1997.81   499.2 1997.54   522.6 1997.08
#Mann= 4 ,-1,0
       0     .05       0  370.54      .1       0   377.4    .045       0
390.1992      .1       0
#XS Ineff= 2 , 0
          340.51 1997.47
Permanent Ineff=
       F       F
Bank Sta=377.4,390.1992
XS Rating Curve= 0 ,0
Exp/Cntr(USF)=0,0
Exp/Cntr=0.3,0.1

Type RM Length L Ch R = 1 ,1011    ,457.9,453.3,451
XS GIS Cut Line= 2
2275239.81015946642310.5768517452275551.79292881642565.923200704
#Sta/Elev= 30
       0  2004.6       5 2002.15    21.1 1989.81    24.8 1988.06    27.7 1987.69
      42  1988.5    61.8 1986.43    67.3 1986.99    73.6 1989.55      78 1990.31
    93.5 1990.46   107.3 1991.77   121.5  1992.3   178.3 1992.85   186.6 1992.47
   201.1 1990.54   212.5 1989.85   220.21987.844   223.8 1986.88   227.9 1986.67
   231.5 1986.94   234.51987.833   238.2 1988.72   248.6 1988.53   256.7  1990.1
   280.7 1990.62   307.2 1992.76   377.8  1994.1   393.3 1993.59   403.2 1993.81
#Mann= 4 ,-1,0
       0      .1       0     140     .05       0   220.2    .045       0
   234.5     .05       0
#XS Ineff= 2 , 0
          124.36 1993.92
Permanent Ineff=
       F       F
Bank Sta=220.2,234.5
XS Rating Curve= 0 ,0
Exp/Cntr(USF)=0,0
Exp/Cntr=0.3,0.1

Type RM Length L Ch R = 1 ,558     ,192.7,178.7,164.6
XS GIS Cut Line= 4
2275015.09858661642624.6942334462275031.82652391642687.587750168
2275100.62065561 642721.074840732275176.76636299642703.135770819
#Sta/Elev= 30
       0 2025.85     4.6 2023.76    17.1 2017.38    21.2 2014.95    29.5 2009.24
      34 2006.44    37.8 2003.63    50.2 1995.84    58.4 1989.73    62.6 1987.27
    65.5 1986.98    68.7    1986    69.9 1985.58    74.4 1983.24    78.8 1981.61
    80.91981.053    83.3 1980.54    96.5 1980.07    99.4 1980.36   102.4 1981.06
   105.4 1981.93   114.4  1982.5   118.9 1983.31   123.4 1983.66   132.7 1983.98
   182.2 1984.77   194.6 1985.24   206.9 1985.51   214.3 1986.09   219.8 1986.34
#Mann= 3 ,-1,0
       0      .1       0    80.9    .045       0   102.4      .1       0
Bank Sta=80.9,102.4
XS Rating Curve= 0 ,0
Exp/Cntr(USF)=0,0
Exp/Cntr=0.3,0.1

Type RM Length L Ch R = 1 ,379     ,77.2,77.2,71.3
XS GIS Cut Line= 6
 2275030.7216152642927.3105598792275073.41790193642809.123459267
2275088.32326549642776.7204950082275108.41310333642747.557827175
2275127.85488188642728.1160486192275170.28518914642711.876467596
#Sta/Elev= 30
       0 1991.23     2.3 1991.88     6.5 1992.32    14.4 1991.35    23.5  1989.8
    27.8 1988.26      32 1985.61    36.3 1984.17    40.5 1982.46    46.5 1978.96
      49 1977.33    51.4 1976.57    52.8 1976.38    53.3 1976.15    62.2 1975.89
    66.1 1976.12   69.19 1976.58    74.9 1977.69    86.7 1980.91    90.3 1981.43
    98.5 1982.07   112.8 1982.55     122 1982.44   143.2 1982.87   178.1 1983.22
   202.1 1983.26     238 1984.32   246.9  1984.8   259.4 1985.79   269.9 1986.13
#Mann= 5 ,-1,0
       0     .06       0    51.4    .045       0   69.19     .07       0
     110     .06       0  224.24      .1       0
Bank Sta=51.4,69.19
XS Rating Curve= 0 ,0
Exp/Cntr(USF)=0,0
Exp/Cntr=0.3,0.1

Type RM Length L Ch R = 1 ,302     ,74.6,81.9,97.2
XS GIS Cut Line= 6
2275077.15427233 642975.884166592275116.83787403642863.560439223
2275131.09517831642827.2691192522275157.01754972642799.402569989
2275208.86229253642759.2228943082275250.33808678642733.948582186
#Sta/Elev= 30
       0 1980.73     7.6 1980.95    13.9 1980.96      17 1980.81    20.2 1980.21
    26.4 1977.96    29.6 1977.06    32.7 1976.43    36.8 1976.01      41  1975.8
    54.6 1975.99   60.181976.429      64 1977.07    70.7 1978.85    73.5 1979.11
    82.9 1979.34    95.4 1980.19   100.4 1980.34   108.9 1980.08   117.4 1979.15
   128.3 1978.76   196.2  1978.7   211.4  1978.9   225.9 1978.59   232.5 1978.76
   273.4 1978.74   279.7 1979.31     286 1981.19   289.1 1981.95   310.3 1983.08
#Mann= 4 ,-1,0
       0      .1       0    32.7    .045       0   60.18     .07       0
  158.12     .06       0
#XS Ineff= 2 , 0
                          102.09         1981.66
Permanent Ineff=
       F       F
Bank Sta=32.7,60.18
XS Rating Curve= 0 ,0
Exp/Cntr(USF)=0,0
Exp/Cntr=0.3,0.1

Type RM Length L Ch R = 1 ,220     ,141.6,148.2,152.9
XS GIS Cut Line= 3
2275054.77065927642982.7697108322275105.94507151643013.582164302
2275192.68754463642990.690371226
#Sta/Elev= 30
       0 1985.08     1.6 1985.41     2.8 1985.27     8.6 1983.19    14.4 1981.94
    20.3 1980.81    29.7  1979.9    35.7 1978.93      39 1978.22    43.4 1976.91
    49.4 1976.02      53 1975.24    57.7 1975.05      62 1976.13    66.2 1976.58
    74.5 1976.77    78.6 1976.48    81.11975.351    82.7 1974.68    86.9 1974.25
    95.1 1974.27     1001975.391   103.4 1976.81   107.5 1977.56   111.7 1977.66
   115.8 1977.01     120 1977.44   132.4 1981.78   136.5 1982.37   149.4 1982.55
#Mann= 3 ,-1,0
       0      .1       0    81.1    .045       0     100      .1       0
#XS Ineff= 2 , 0
                           109.4         1979.13
Permanent Ineff=
       F       F
Bank Sta=81.1,100
XS Rating Curve= 0 ,0
Exp/Cntr(USF)=0,0
Exp/Cntr=0.3,0.1

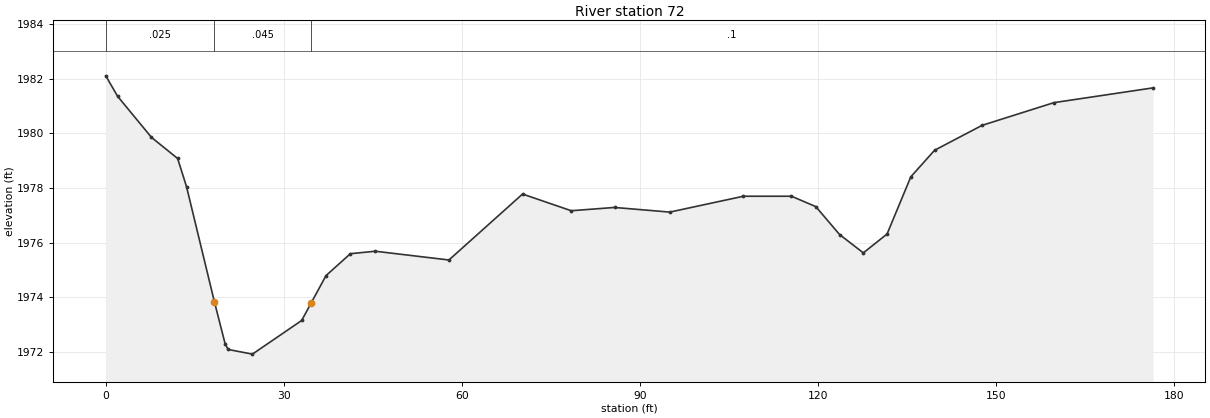
Type RM Length L Ch R = 1 ,72      ,,,
XS GIS Cut Line= 4
2275037.04159299643069.5038280312275044.53110153643079.739489696
2275140.86138404 643104.815058362275204.86735544643100.177243289
#Sta/Elev= 30
       0  1982.1       2 1981.35     7.7 1979.85    12.1 1979.08    13.6 1978.05
    18.31973.839    20.1 1972.31    20.6  1972.1    24.7 1971.93      33 1973.16
    34.61973.803    37.1  1974.8    41.2  1975.6    45.4 1975.69    57.8 1975.37
    70.2 1977.78    78.4 1977.17    85.7 1977.29      95 1977.12   107.4  1977.7
   115.5  1977.7   119.6 1977.32   123.6  1976.3   127.6 1975.63   131.6 1976.32
   135.6 1978.41   139.6 1979.38   147.6 1980.29   159.7 1981.12   176.4 1981.66
#Mann= 3 ,-1,0
       0    .025       0    18.3    .045       0    34.6      .1       0
Bank Sta=18.3,34.6
XS Rating Curve= 0 ,0
Exp/Cntr(USF)=0,0
Exp/Cntr=0.3,0.1
LCMann Table=0

Chan Stop Cuts=-1
Use User Specified Reach Order=0
Composite Channel Slope=5